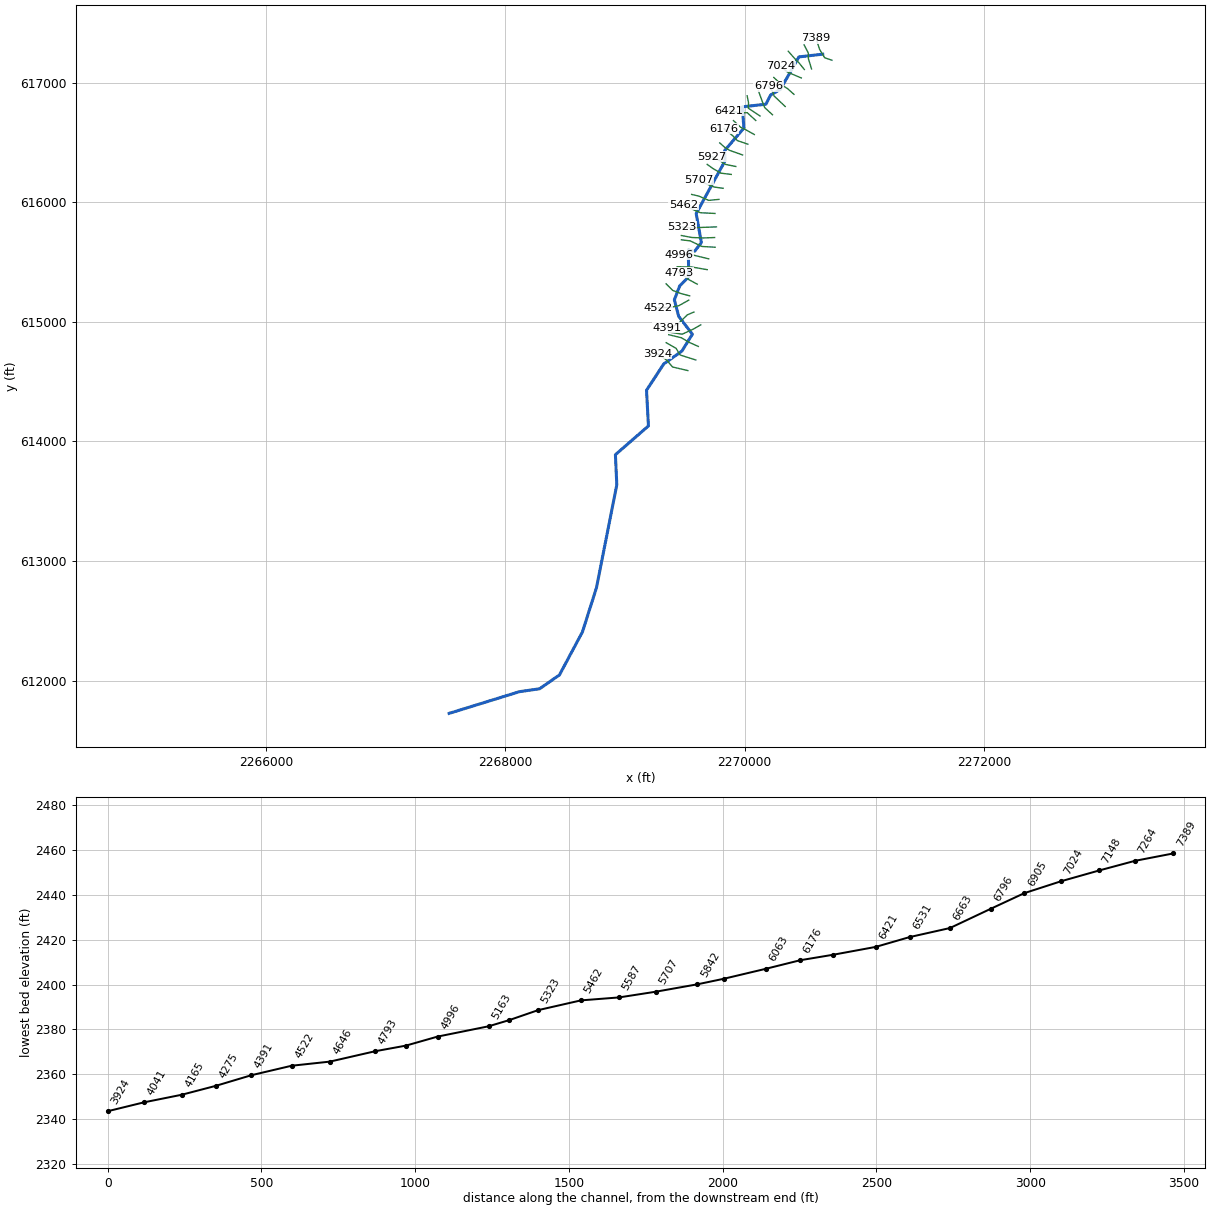
--- LAURELRN5.prj (project) ---

Proj Title=LAURELRN5
Current Plan=p01
Default Exp/Contr=0,0
English Units
Geom File=g01
Flow File=f01
Plan File=p01
BEGIN DESCRIPTION:
----------MODEL BY WOOD PLC 2022----------
AFH study
Randolph County, WV
HEC-RAS Version: RAS 6.2
Vertical Datum: NAVD88
Projection: NAD 1983 StatePlane West Virginia S FIPS 4702 (US Feet)
Terrain: 1-meter LIDAR (FEMA Region III 3DEP collected 2016-2018)
Land Use: 2019 NLCD
Hydrologic Method:
WV SIR2010-5033 regression equations
Additional Model Notes:
None
END DESCRIPTION:
DSS Export Rating Curves= 0
DSS Export Rating Curve Sorted= 0
DSS Export Volume Flow Curves= 0
DXF OffsetX= 0
DXF OffsetY= 0
DXF ScaleX= 0
DXF ScaleY= 0

--- LAURELRN5.p01 (plan) ---

Plan Title=Floodplain
Program Version=6.20
Short Identifier=Floodplain
Geom File=g01
Flow File=f01
Subcritical Flow
K Sum by GR= 0
Std Step Tol= 0.01
Critical Tol= 0.01
Num of Std Step Trials= 20
Max Error Tol= 0.3
Flow Tol Ratio= 0.001
Split Flow NTrial= 30
Split Flow Tol= 0.02
Split Flow Ratio= 0.02
Log Output Level= 0
Friction Slope Method= 1
Unsteady Friction Slope Method= 2
Unsteady Bridges Friction Slope Method= 1
Parabolic Critical Depth
Global Vel Dist= 0 , 0 , 0
Global Log Level= 0
CheckData=True
Encroach Param=-1 ,0,0, 0
Mapping Interval=1HOUR
Computation Time Step Use Courant=        0
Computation Time Step Use Time Series=    0
Computation Time Step Count To Double=0
Computation Time Step Max Doubling=0
Computation Time Step Max Halving=0
Computation Time Step Residence Courant=0
Run HTab= 0
Run UNet= 0
Run Sediment= 0
Run PostProcess= 0
Run WQNet= 0
Run RASMapper=-1
UNET Theta= 0
UNET Theta Warmup= 0
UNET ZTol= 0
UNET ZSATol= 0
UNET MxIter= 0
UNET Max Iter WO Improvement= 0
UNET MaxInSteps= 0
UNET DtIC= 0
UNET DtMin= 0
UNET MaxCRTS= 0
UNET WFStab= 0
UNET SFStab= 0
UNET WFX= 1
UNET SFX= 1
UNET Gravity=32.174
UNET 1D Methodology=Finite Difference
UNET DSS MLevel= 1
UNET Pardiso=0
UNET DZMax Abort= 0
UNET Use Existing IB Tables= 0
UNET Froude Reduction=False
UNET Froude Limit= 0
UNET Froude Power= 0
UNET D1 Cores= 0
UNET WindReference=Eulerian
UNET WindDragFormulation=Hsu (1988)
UNET D2 Coriolis=0
UNET D2 Cores= 0
UNET D2 Theta= 1
UNET D2 Theta Warmup= 1
UNET D2 Z Tol= 0.01
UNET D2 Volume Tol= 0.01
UNET D2 Max Iterations= 20
UNET D2 Equation= 0
UNET D2 RampUpFraction=0.1
UNET D2 TimeSlices= 1
UNET D2 Turbulence Formulation=Non-Conservative (original)
UNET D2 Eddy Viscosity=0.3
UNET D2 Transverse Eddy Viscosity=0.1
UNET D2 Smagorinsky Mixing=0
UNET D2 BCVolumeCheck=0
UNET D2 Cores=0
UNET D2 SolverType=PARDISO (Direct)
UNET D2 Minimum Iterations= 2147483647
UNET D2 Maximum Iterations= 2147483647
UNET D2 Restart Number= 10
UNET D2 Relaxation Coeff=1.3
UNET D2 SOR Precondition Iterations= 10
UNET D2 ILUT Maximum Fill= 8
UNET D2 ILUT Tolerance=1E-08
UNET D1D2 MaxIter= 0
UNET D1D2 ZTol=0.01
UNET D1D2 QTol=0.1
UNET D1D2 MinQTol=1
Write IC File= 0
Write IC File at Fixed DateTime=0
Write IC File at Sim End=0
Echo Input=False
Echo Parameters=False
Echo Output=False
Write Detailed= 0
HDF Write Warmup=0
HDF Write Time Slices=0
HDF Flush=0
HDF Compression= 1
HDF Chunk Size= 1
HDF Spatial Parts= 1
HDF Use Max Rows=0
HDF Fixed Rows= 1
Calibration Method= 0
Calibration Iterations= 20
Calibration Max Change=0.05
Calibration Tolerance=0.2
Calibration Maximum=1.5
Calibration Minimum=0.5
Calibration Optimization Method= 1
WQ AD Non Conservative
WQ ULTIMATE=-1
WQ Max Comp Step=1HOUR
WQ Output Interval=15MIN
WQ Output Selected Increments= 0
WQ Output face flow=0
WQ Output face velocity=0
WQ Output face area=0
WQ Output face dispersion=0
WQ Output cell volume=0
WQ Output cell surface area=0
WQ Output cell continuity=0
WQ Output cumulative cell continuity=0
WQ Output face conc=0
WQ Output face dconc_dx=0
WQ Output face courant=0
WQ Output face peclet=0
WQ Output face adv mass=0
WQ Output face disp mass=0
WQ Output cell mass=0
WQ Output cell source sink temp=0
WQ Output nsm pathways=0
WQ Output nsm derived pathways=0
WQ Create Restart=0
WQ Fixed Restart=0
WQ System Summary=0
WQ Write To DSS=0
Sorting and Armoring Iterations= 10
XS Update Threshold= 0.02
Bed Roughness Predictor= 0
Hydraulics Update Threshold= 0.02
Energy Slope Method= 1
Volume Change Method= 1
Sediment Retention Method= 0
Sediment TS Multiplier= 1
Warm Up Method= 0
XS Weighting Method= 0
Number of US Weighted Cross Sections= 1
Number of DS Weighted Cross Sections= 1
Upstream XS Weight=0
Main XS Weight=1
Downstream XS Weight=0
Number of DS XS's Weighted with US Boundary= 1
Upstream Boundary Weight= 1
Weight of XSs Associated with US Boundary= 0
Number of US XS's Weighted with DS Boundary= 1
Downstream Boundary Weight= 0.5
Weight of XSs Associated with DS Boundary= 0.5
Percentile Method= 0
Sediment Output Level= 3
Mass or Volume Output= 0
Output Increment Type= 1
Profile and TS Output Increment= 1
Transport Output Increment 1
XS Output Flag= 0
XS Output Increment= 10
Read HDF5 Sediment Hotstart= 0
Sediment Hotstart Type= 0
Write Gradation File= 0
Read Gradation Hotstart= 0
Write HDF5 File= 1
Write Binary Output= 1
Write DSS Sediment File= 0
DSS Sediment Output Type= 1
SV Curve= 0
Specific Gage Flag= 0
Subcell Erosion Methods= 0
Subcell Deposition Methods= 0
Advection Scheme= 1
Matrix Solver= 0
Implicit Weighting Factor= 1
Maximum Outer Loop Convergence Iterations= 5
Convergence Maximum Absolute= 0.001
Convergence RMSE= 0.0001
Grain Fractions Max Abs Error= 0.001
Max Subgrid Regions= 1
Max Subgrid Length Scale= 3.402823E+38
Initial Layer Thickness= 3.402823E+38
Min Layer Thickness= 3.402823E+38
Max Layer Thickness= 3.402823E+38
Number of Layers= 5

--- LAURELRN5.f01 (steady flow) ---

Flow Title=Flow
Program Version=6.20
Number of Profiles= 1
Profile Names=P100yr
River Rch & RM=LAURELRN5,Main,7389
     357
River Rch & RM=LAURELRN5,Main,4522
     443
River Rch & RM=LAURELRN5,Main,2107
     501
Boundary for River Rch & Prof#=LAURELRN5,Main            , 1
Up Type= 0
Dn Type= 3
Dn Slope=0.03677
DSS Import GetInterval= 0
DSS Import GetPeak= 0
DSS Import FillOption= 0

--- LAURELRN5.g01 (geometry) ---

Geom Title=Geometry
Program Version=6.20

River Reach=LAURELRN5       ,Main
Reach XY= 30
2270652.47614156617237.973707289     2270453.715      617215.162
2270299.28800003616943.8079999982270217.52700001 616896.74500002
2270178.71500003616819.7629999972269981.26500003616797.566000015
2269993.99300005616619.7630000112269832.88200004616431.568000019
2269838.04190788616348.5183870052269595.39614797615905.112891704
2269638.85663989615662.7130749822269583.56172204615591.154803678
2269529.59712626615598.5595116472269533.33799998      615377.044
2269457.47699998615299.4790000022269413.20600002615183.159999996
2269449.66399999615045.1390000132269563.53900003614896.285999998
2269475.91200003614754.7810000182269324.98100004614647.886000022
2269180.56699999614427.9520000222269196.62700002614129.342000008
2268920.58400002613888.4550000132268932.26699999613636.936000004
2268762.12800001612774.9570000172268644.94099998612406.033000022
2268453.10000001612046.658000007     2268287.302611931.207000002
2268118.89900005611906.900999993     2267531.366      611725.396

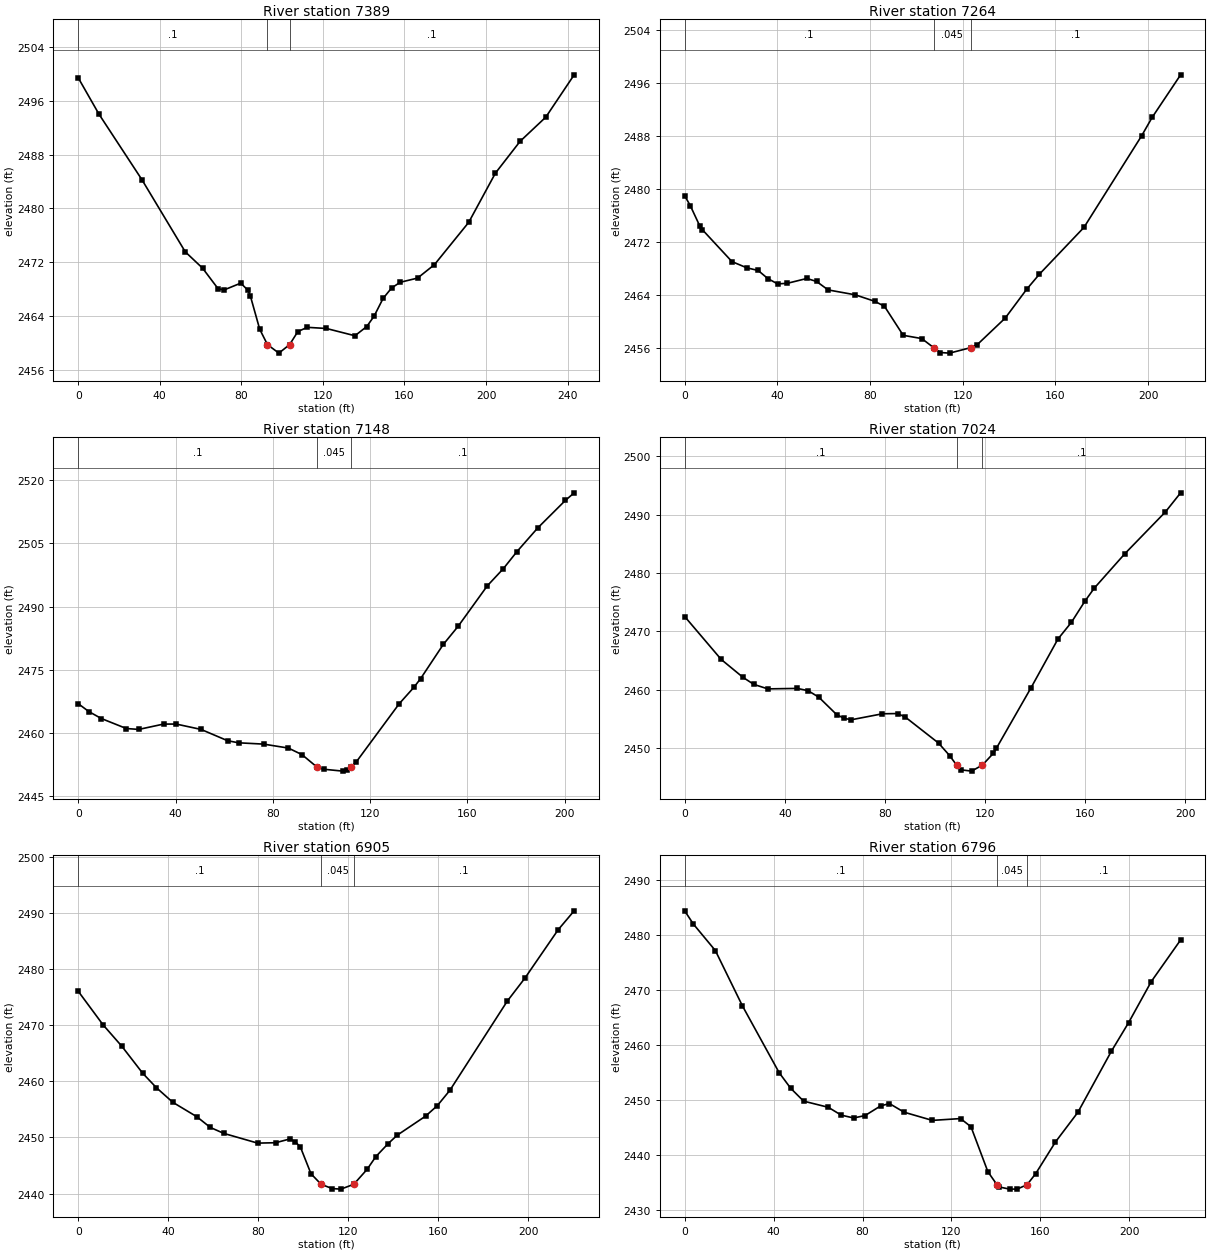
Type RM Length L Ch R = 1 ,7389    ,128.8,125.6,122.7
XS GIS Cut Line= 4
2270729.84294779617187.2199571922270668.79237014617208.198171757
 2270626.0587305617279.2367447932270597.02340145617370.457773913
#Sta/Elev= 30
       0 2499.39    10.2 2493.98    31.2 2484.28    52.5 2473.55      61 2471.12
    68.6 2468.07    71.5 2467.89    79.7  2468.9    83.2 2467.86    84.4 2467.02
      89 2462.06   92.792459.778    98.4 2458.51  103.682459.779   107.7 2461.71
   112.3 2462.34   121.7 2462.17   135.7 2461.09   141.5 2462.46   145.1    2464
   149.5 2466.63   153.7 2468.19   157.9 2469.03   166.4 2469.65   174.7 2471.65
   191.5 2477.93   204.6 2485.24   216.7 2489.96   229.3 2493.55   243.2 2499.83
#Mann= 3, -1 ,  0
       0     0.1       0   92.79   0.045       0  103.68     0.1       0
Bank Sta=92.79,103.68
XS Rating Curve= 0 ,0
Exp/Cntr=0.3,0.1

Type RM Length L Ch R = 1 ,7264    ,108.7,116.3,120.4
XS GIS Cut Line= 4
2270559.34993684617114.8621226882270532.98310377617199.860466144
2270532.98310377617246.696288048 2270496.9021743617316.082690869
#Sta/Elev= 30
       0 2478.96     2.4 2477.48     6.6 2474.33     7.6 2473.84    20.4 2469.01
    26.8 2468.07    31.7 2467.67    35.9 2466.44    40.1 2465.64    44.3 2465.73
    52.7 2466.46    56.9 2466.01    61.9 2464.73    73.6 2463.99      82 2463.01
    86.2 2462.26    94.3 2457.87   102.3 2457.38  107.462456.003   110.3 2455.27
   114.3 2455.18  123.352456.001   126.3 2456.48   138.3 2460.47   147.6 2464.84
   153.1 2467.12   172.3 2474.18   197.2 2488.03   201.7 2490.79     214 2497.23
#Mann= 3, -1 ,  0
       0     0.1       0  107.46   0.045       0  123.35     0.1       0
Bank Sta=107.46,123.35
XS Rating Curve= 0 ,0
Exp/Cntr(USF)=0,0
Exp/Cntr=0.3,0.1

Type RM Length L Ch R = 1 ,7148    ,120.6,123.4,125.2
XS GIS Cut Line= 4
2270499.13530871 617109.773679692270451.60946613617169.002305347
2270419.56456268617200.4215581172270364.61257078 617262.67021785
#Sta/Elev= 30
       0 2466.92     4.4 2465.03     9.5 2463.39    19.8 2461.01    24.9  2460.8
    35.1 2462.07    40.3 2462.07    50.5  2460.8    61.4 2458.12    65.9 2457.62
    76.2 2457.31    86.4 2456.37      92 2454.81   98.282451.796   101.1 2451.33
   108.8 2450.89   110.5 2451.13  112.082451.795   114.4 2453.14     132 2466.92
     138 2470.79   140.8 2472.89   150.1 2480.99   156.2  2485.3   168.2 2494.92
   174.8    2499   180.4 2503.06   188.9 2508.65   200.3 2515.21   203.9 2517.01
#Mann= 3, -1 ,  0
       0     0.1       0   98.28   0.045       0  112.08     0.1       0
Bank Sta=98.28,112.08
XS Rating Curve= 0 ,0
Exp/Cntr=0.3,0.1

Type RM Length L Ch R = 1 ,7024    ,121.3,119.6,119.2
XS GIS Cut Line= 4
2270473.62540122617039.2002609072270387.83217755617075.207801337
2270355.94679353617089.484838955 2270303.5976556617136.123161838
#Sta/Elev= 30
       0 2472.55    14.6  2465.2    23.3 2462.14    27.6 2460.94    33.2 2460.17
      45 2460.25    49.3 2459.86    53.6 2458.74    60.7 2455.77    63.7 2455.13
    66.6 2454.89      79 2455.91    85.1 2455.95    88.2 2455.32   101.4  2450.9
   105.8 2448.77  108.622447.133   110.2 2446.33   114.6  2446.1  118.932447.136
   123.3 2449.15   124.5    2450   138.4  2460.4   149.1  2468.7   154.5 2471.57
   159.8 2475.13   163.6  2477.4   175.9 2483.33     192 2490.43   198.1 2493.71
#Mann= 3, -1 ,  0
       0     0.1       0  108.62   0.045       0  118.93     0.1       0
Bank Sta=108.62,118.93
XS Rating Curve= 0 ,0
Exp/Cntr(USF)=0,0
Exp/Cntr=0.3,0.1

Type RM Length L Ch R = 1 ,6905    ,114.5,108.5,104.2
XS GIS Cut Line= 4
2270412.35654552616902.0101615212270358.82759227616949.990508146
2270310.42612211616980.4934184912270244.24425684617043.283082019
#Sta/Elev= 30
       0 2476.06      11 2470.09    19.4 2466.24    28.7 2461.42    34.7 2458.88
      42 2456.27    52.7 2453.69    58.7 2451.78    64.7 2450.72    79.7 2448.99
    87.7 2449.06    93.9 2449.72    96.4 2449.25    98.7 2448.29   103.4 2443.53
   107.9 2441.65   112.8 2440.89   116.7 2440.79   122.42441.651   128.3  2444.3
   132.2 2446.58   137.7 2448.91   141.7  2450.4   154.3  2453.8   159.5 2455.66
   165.1  2458.4   190.6  2474.3   198.4 2478.38   213.2 2487.02   220.3 2490.39
#Mann= 3, -1 ,  0
       0     0.1       0   107.9   0.045       0   122.4     0.1       0
Bank Sta=107.9,122.4
XS Rating Curve= 0 ,0
Exp/Cntr=0.3,0.1

Type RM Length L Ch R = 1 ,6796    ,133.1,133.3,130.7
XS GIS Cut Line= 4
2270339.01882131616800.5569453572270245.46689898616889.274339606
2270236.44666662616922.2328809452270200.20726203616970.113041712
#Sta/Elev= 30
       0 2484.43     3.9 2482.03    13.8 2477.21      26 2467.14    42.5 2455.02
    47.7 2452.18    53.5 2449.85    64.6 2448.73    70.4 2447.31      76 2446.79
    81.1 2447.22    88.1 2448.97    92.1 2449.41    98.7 2447.84   111.4 2446.35
   124.1 2446.68   128.8 2445.19   136.4 2437.02  140.472434.669   141.3 2434.27
   146.2 2433.86   149.6 2433.87  154.042434.668   157.9 2436.67   166.8 2442.43
   176.9 2447.83   191.9 2458.88   199.7 2464.11   209.9 2471.58   223.1 2479.14
#Mann= 3, -1 ,  0
       0     0.1       0  140.47   0.045       0  154.04     0.1       0
Bank Sta=140.47,154.04
XS Rating Curve= 0 ,0
Exp/Cntr(USF)=0,0
Exp/Cntr=0.3,0.1

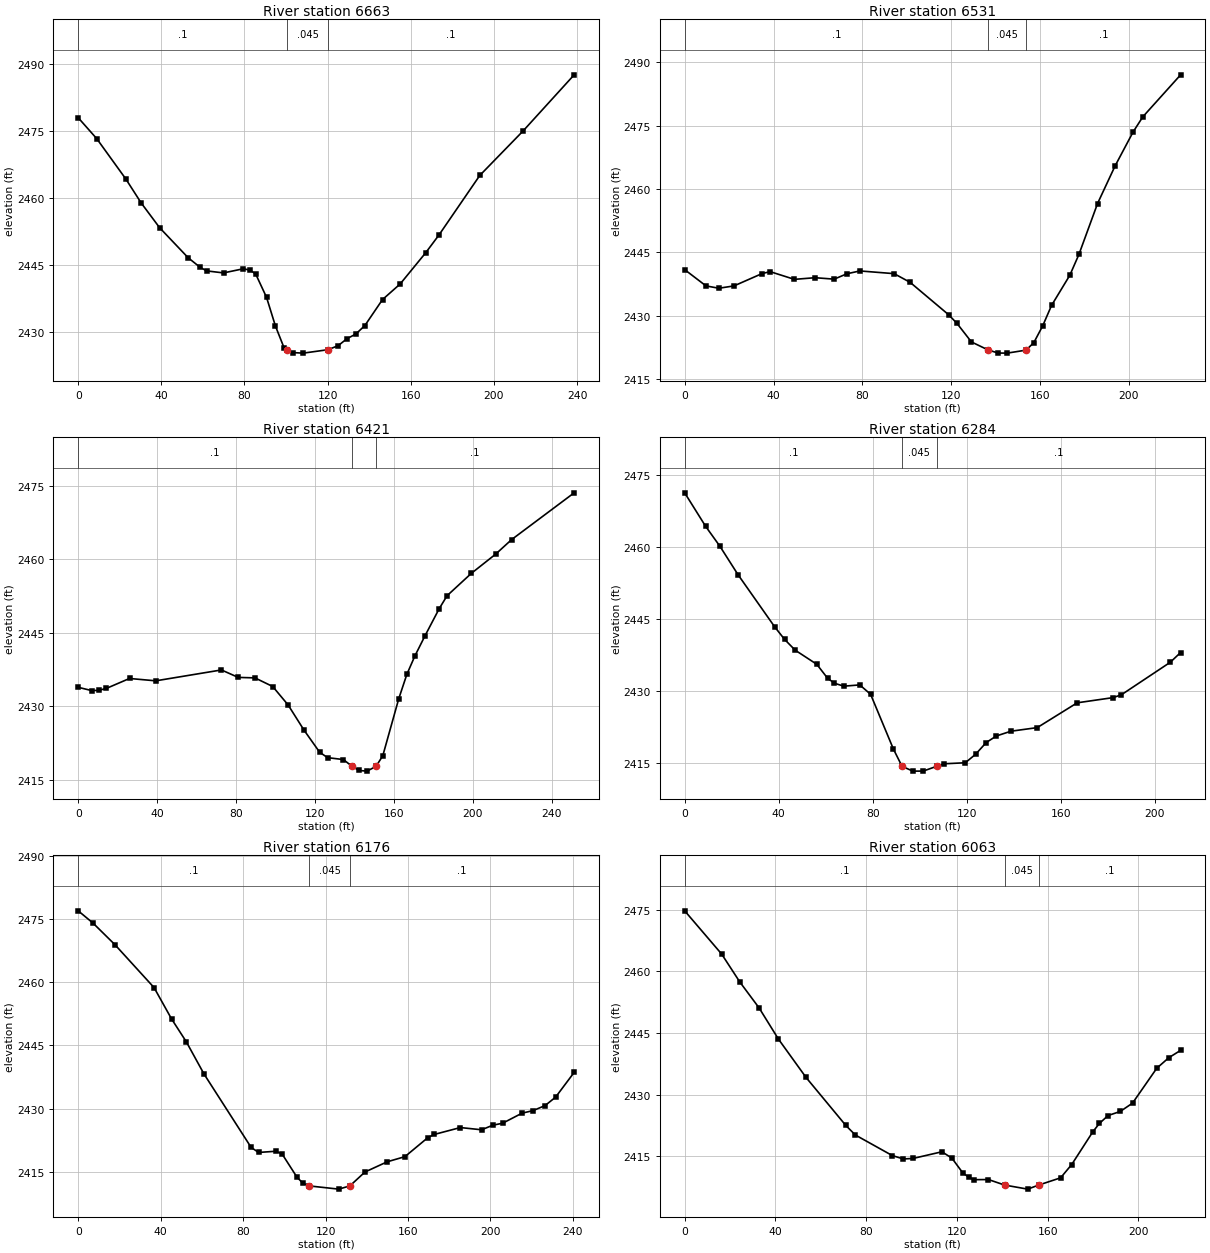
Type RM Length L Ch R = 1 ,6663    ,134.8,131.6,126.5
XS GIS Cut Line= 4
2270232.93752686616731.1614349922270167.88585637616791.439666977
2270150.39831905616835.1212994642270115.46263689616931.902705055
#Sta/Elev= 30
       0 2477.87     8.9  2473.2    22.9 2464.18    30.3 2458.81    39.2 2453.26
    52.9 2446.56    58.6 2444.44    61.8 2443.62    69.9 2443.17    79.5  2444.1
    82.8 2443.77    85.4 2442.91    90.6 2437.71    94.9 2431.27      99 2426.46
  100.512425.989   103.5 2425.34   108.3 2425.23  120.062425.989     125 2426.88
   129.3 2428.45   133.6 2429.52   137.9 2431.39   146.4 2437.21   154.9  2440.7
   167.2 2447.69   173.5 2451.61   193.2 2464.97   214.1 2474.95   238.6 2487.47
#Mann= 3, -1 ,  0
       0     0.1       0  100.51   0.045       0  120.06     0.1       0
Bank Sta=100.51,120.06
XS Rating Curve= 0 ,0
Exp/Cntr=0.3,0.1

Type RM Length L Ch R = 1 ,6531    ,90.9,110,116.1
XS GIS Cut Line= 4
2270129.24505253616720.8823724152270030.53960728616786.686002586
2270032.88973693616831.3384659172270021.13908868616890.091707141
#Sta/Elev= 30
       0 2440.93     9.6 2437.08    15.4 2436.53    22.2 2437.08    34.9 2440.01
    38.5 2440.45    49.4 2438.63    58.7 2439.02    67.3 2438.68    73.1 2439.96
    78.9 2440.62    94.3 2439.98   101.5 2437.93   118.8 2430.28   122.6 2428.22
   129.1 2423.83  136.782421.891   141.2  2421.2   145.2 2421.18  153.712421.889
   157.2 2423.66   161.2 2427.63   165.2 2432.48   173.4 2439.59   177.5 2444.51
   185.9 2456.57   193.8 2465.47   201.9 2473.49   206.3 2477.09   223.3 2487.01
#Mann= 3, -1 ,  0
       0     0.1       0  136.78   0.045       0  153.71     0.1       0
Bank Sta=136.78,153.71
XS Rating Curve= 0 ,0
Exp/Cntr(USF)=0,0
Exp/Cntr=0.3,0.1

Type RM Length L Ch R = 1 ,6421    ,142.2,137.4,134.5
XS GIS Cut Line= 4
2270093.21244144616683.6378041072270021.43501726616749.035626519
2269960.76344829616746.5177489372269869.19436213616765.754828212
#Sta/Elev= 30
       0 2433.91     6.8 2433.24    10.3 2433.29    14.2 2433.67      26 2435.71
    39.3 2435.23    72.6 2437.45    81.1 2435.93    89.6 2435.83    98.6 2434.07
   106.4 2430.31   114.4 2425.21   122.4 2420.66   126.4 2419.56   134.4 2419.17
  138.872417.778   142.4 2416.94   146.4 2416.81  150.972417.778   154.4 2419.95
   162.5  2431.6   166.6 2436.56   170.7 2440.33   175.8 2444.42     183 2449.96
     187  2452.6   199.3 2457.16   211.6 2461.07   219.7 2464.04   251.4 2473.58
#Mann= 3, -1 ,  0
       0     0.1       0  138.87   0.045       0  150.97     0.1       0
Bank Sta=138.87,150.97
XS Rating Curve= 0 ,0
Exp/Cntr=0.3,0.1

Type RM Length L Ch R = 1 ,6284    ,111.4,108.1,106
XS GIS Cut Line= 4
2270081.23067413616566.0974241892270008.89368354616606.549030772
2269966.53847194616627.488685945 2269907.0508152616682.217330145
#Sta/Elev= 30
       0 2471.22     8.9 2464.26      15  2460.1    22.7 2454.19    38.3 2443.34
    42.5 2440.74      47  2438.5    56.2 2435.56    60.8 2432.66    63.7 2431.62
    67.7 2431.01    74.5 2431.27    79.1 2429.32    88.8 2417.93   92.482414.333
    97.1 2413.34   101.5 2413.35  107.182414.338   110.5 2414.87   119.4 2415.08
   123.8 2416.86   128.3 2419.29   132.6 2420.65   138.8 2421.64     150 2422.39
     167 2427.55   182.3 2428.63   185.8 2429.22   206.6 2435.98     211 2438.01
#Mann= 3, -1 ,  0
       0     0.1       0   92.48   0.045       0  107.18     0.1       0
Bank Sta=92.48,107.18
XS Rating Curve= 0 ,0
Exp/Cntr(USF)=0,0
Exp/Cntr=0.3,0.1

Type RM Length L Ch R = 1 ,6176    ,110.2,112.3,114.3
XS GIS Cut Line= 4
2270026.99579362616485.4565626622269939.23609953616515.438524538
2269901.85340164616555.1748966782269829.20171499616613.670106653
#Sta/Elev= 30
       0 2476.95     7.2 2474.03    17.8 2468.92    36.8 2458.72    45.3 2451.27
    52.4 2445.89      61 2438.23    83.9 2420.77    87.5 2419.58    96.1 2419.87
      99 2419.15   106.1 2413.73   108.9 2412.32  111.982411.637   126.4 2410.87
  131.792411.636   139.1 2414.93   149.9 2417.36   158.5 2418.58   169.6 2423.09
   172.7 2423.85   185.4 2425.49   195.7 2424.96   201.1 2426.04   205.9 2426.52
   215.3  2428.9   220.7 2429.52   226.5 2430.71   231.6 2432.71   240.6 2438.59
#Mann= 3, -1 ,  0
       0     0.1       0  111.98   0.045       0  131.79     0.1       0
Bank Sta=111.98,131.79
XS Rating Curve= 0 ,0
Exp/Cntr=0.3,0.1

Type RM Length L Ch R = 1 ,6063    ,134.5,136.3,136.5
XS GIS Cut Line= 4
2269983.12782666616395.3897561482269873.67053826616433.990635633
2269829.75891477616462.522196773 2269792.3277259616495.906770626
#Sta/Elev= 30
       0 2474.74    16.3 2464.22    24.3 2457.43    32.8 2451.12    41.3 2443.55
    53.5  2434.2      71 2422.54    75.2 2420.21    91.5  2415.2    96.4 2414.37
   100.7  2414.5   113.4 2416.12   117.8 2414.56   122.6 2410.97   125.2 2409.94
   127.4 2409.33   133.9 2409.36  141.012408.021   151.2 2407.03  156.062408.022
   165.7 2409.78   170.6 2413.02   179.9 2420.98   182.8 2423.01   186.6 2424.93
     192 2425.93   197.4 2427.95   208.1 2436.45   213.4 2439.01   218.6 2440.79
#Mann= 3, -1 ,  0
       0     0.1       0  141.01   0.045       0  156.06     0.1       0
Bank Sta=141.01,156.06
XS Rating Curve= 0 ,0
Exp/Cntr(USF)=0,0
Exp/Cntr=0.3,0.1

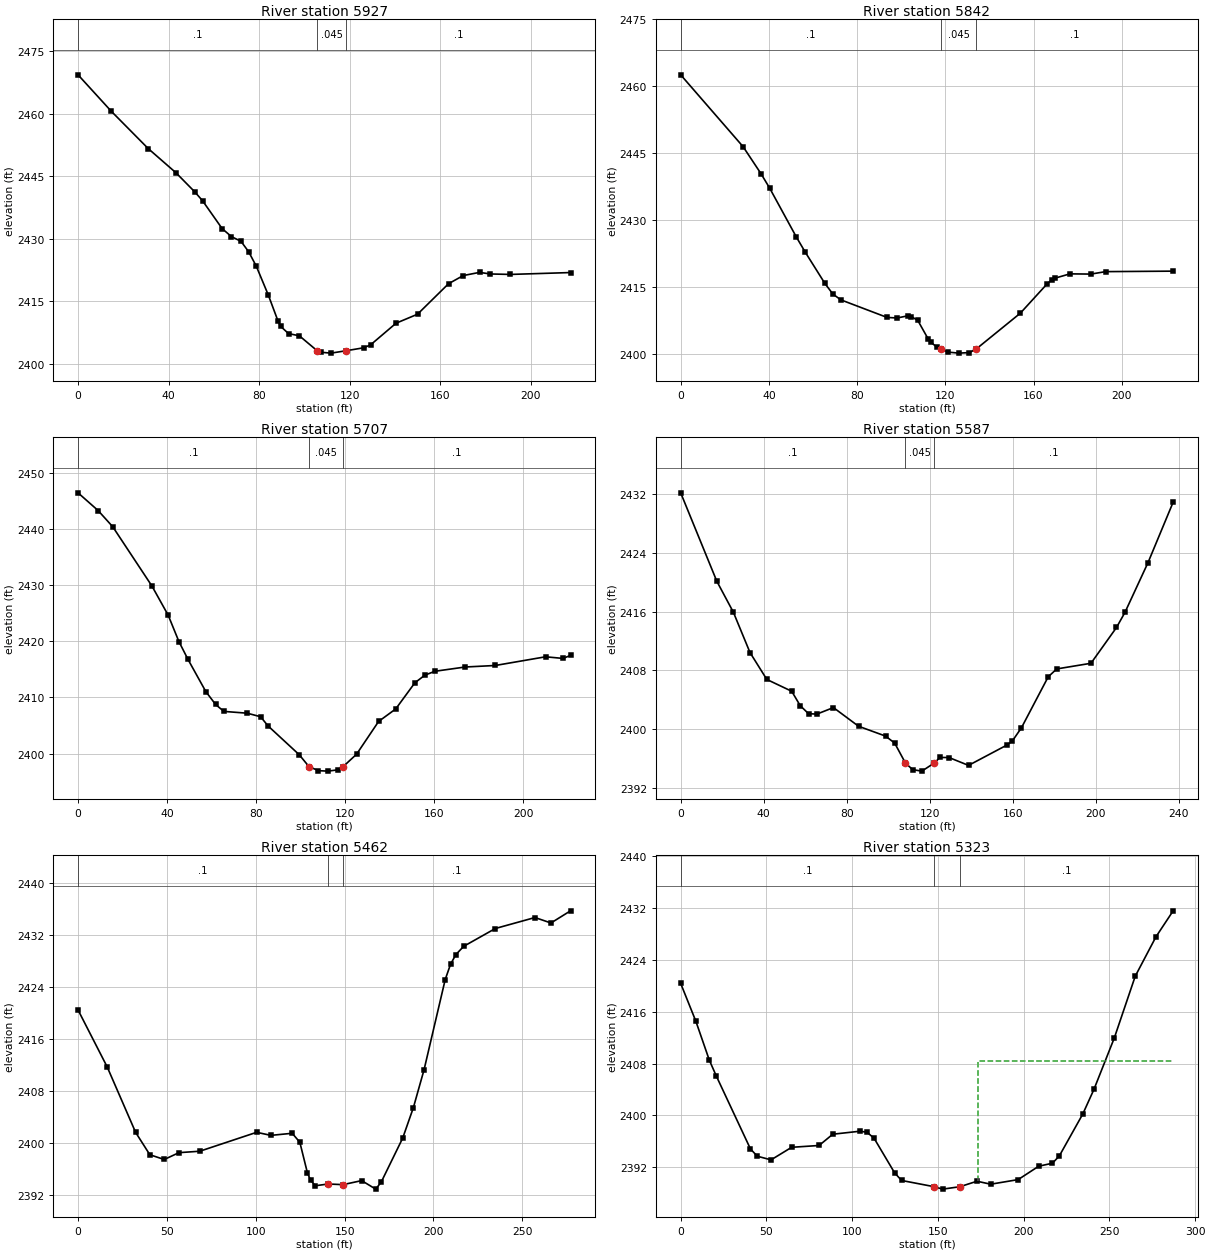
Type RM Length L Ch R = 1 ,5927    ,85.1,85.4,85.7
XS GIS Cut Line= 4
2269926.60174355616298.7914447132269840.75492842616316.137284503
 2269786.1064902616351.1296842632269728.66302611 616381.91392846
#Sta/Elev= 30
       0 2469.33    14.7 2460.59      31 2451.65    43.3 2445.83    51.6 2441.25
      55 2439.15    63.7 2432.44    67.8 2430.53      72 2429.41    75.4  2426.9
    78.8  2423.4    84.1 2416.49    88.3 2410.38    89.5 2409.03      93 2407.29
    97.8 2406.75   105.6  2403.2   107.3 2402.81   111.8  2402.6   118.62403.186
   126.3 2403.89   129.3  2404.6   140.5 2409.77     150 2411.93   163.7 2419.24
   170.2  2421.2   177.4 2421.96   182.2 2421.58     191 2421.47   217.6 2421.92
#Mann= 3, -1 ,  0
       0     0.1       0   105.6   0.045       0   118.6     0.1       0
Bank Sta=105.6,118.6
XS Rating Curve= 0 ,0
Exp/Cntr=0.3,0.1

Type RM Length L Ch R = 1 ,5842    ,133.2,134.4,135.4
XS GIS Cut Line= 4
2269888.26887252  616232.4087121 2269801.3140755 616242.98429552
2269735.91455013616281.6496860642269687.34406815616316.342887474
#Sta/Elev= 30
       0 2462.53    28.3 2446.42    36.4 2440.38    40.3 2437.17    52.5 2426.12
    56.5 2422.76    65.4 2415.75      69 2413.39    72.6 2412.09    93.6 2408.14
    98.2 2408.02   102.9  2408.5   104.6 2408.32   107.5 2407.48   112.2 2403.33
   113.4 2402.61   116.3 2401.41  117.922401.064   121.4 2400.36   126.1 2400.14
   130.9 2400.26     1342401.063     154 2409.09   165.9 2415.53   168.2 2416.58
   169.6 2416.93   176.5 2417.91     186 2417.86   192.7 2418.41   223.3 2418.52
#Mann= 3, -1 ,  0
       0     0.1       0  117.92   0.045       0     134     0.1       0
Bank Sta=117.92,134
XS Rating Curve= 0 ,0
Exp/Cntr(USF)=0,0
Exp/Cntr=0.3,0.1

Type RM Length L Ch R = 1 ,5707    ,120.2,120.5,120.1
XS GIS Cut Line= 4
 2269821.1032679616116.600117817 2269745.1110577616126.826775027
2269675.08884728616155.8833249442269614.34444503616187.918532959
#Sta/Elev= 30
       0 2446.44       9 2443.29    15.6 2440.39    33.2 2429.83    40.5 2424.63
    45.3 2419.95    49.4 2416.75    57.4 2411.03    61.8 2408.73    65.5  2407.5
      76 2407.18      82 2406.55    85.3 2404.93    99.3  2399.8  103.72 2397.67
     108 2396.94   112.3 2396.86   116.7 2397.09     119 2397.64   125.1 2399.87
     135 2405.71   142.7 2407.94   151.3  2412.6   155.8 2413.96   160.3 2414.65
   173.9 2415.41   187.4 2415.68     210 2417.23   217.8 2416.94   221.2 2417.47
#Mann= 3, -1 ,  0
       0     0.1       0  103.72   0.045       0     119     0.1       0
Bank Sta=103.72,119
XS Rating Curve= 0 ,0
Exp/Cntr=0.3,0.1

Type RM Length L Ch R = 1 ,5587    ,124.4,124.3,123.6
XS GIS Cut Line= 4
2269785.47385409616023.6220727192269699.81162839616015.484161277
2269618.00420284616051.0339849452269557.61233372616065.168252186
#Sta/Elev= 30
       0 2432.17    17.4 2420.14    25.4 2415.91    33.4 2410.43    41.5 2406.77
    53.5 2405.16    57.6  2403.2    61.6 2402.11    65.6 2402.05    73.6 2402.94
    85.7  2400.4    98.7 2399.06   103.1 2398.11   108.3 2395.39   111.8 2394.49
   116.2 2394.29  122.282395.406   124.9 2396.15   129.3 2396.14   138.7 2395.07
     157 2397.81   159.8 2398.39   164.2 2400.19   177.1 2407.13   181.2  2408.2
   197.7 2408.97     210 2413.84   214.1 2415.91   225.2 2422.68   237.3  2430.9
#Mann= 3, -1 ,  0
       0     0.1       0   108.3   0.045       0  122.28     0.1       0
Bank Sta=108.3,122.28
XS Rating Curve= 0 ,0
Exp/Cntr(USF)=0,0
Exp/Cntr=0.3,0.1

Type RM Length L Ch R = 1 ,5462    ,135.7,139.1,139.5
XS GIS Cut Line= 4
2269752.57339083615906.0210352232269630.87577935615911.968220501
  2269575.537208615935.5430570772269490.24942978615977.701545417
#Sta/Elev= 30
       0 2420.52    16.4 2411.76    32.4 2401.69    40.4 2398.25    48.5 2397.52
    56.8 2398.57    68.5 2398.79   100.5  2401.7   108.5 2401.23   120.5 2401.55
   124.8 2400.17   129.1 2395.42   130.9 2394.32   133.5 2393.48  140.812393.749
   149.1 2393.65   159.6 2394.27   167.5 2392.96   170.6 2394.05   182.7 2400.82
   188.7 2405.51   194.7 2411.33   206.6  2425.2   209.6 2427.55   212.6 2429.04
     217 2430.31   234.8 2433.05   257.1 2434.74   266.1  2433.9   277.1 2435.77
#Mann= 3, -1 ,  0
       0     0.1       0  140.81   0.045       0   149.1     0.1       0
Bank Sta=140.81,149.1
XS Rating Curve= 0 ,0
Exp/Cntr=0.3,0.1

Type RM Length L Ch R = 1 ,5323    ,94.3,93.4,93.2
XS GIS Cut Line= 3
2269764.85447625615793.6974586722269540.85017301615785.465741619
 2269478.3182803615793.206806859
#Sta/Elev= 30
       0 2420.38     8.9  2414.5    16.7 2408.53    20.7 2406.12    40.7 2394.81
    44.7 2393.69    52.7 2393.13    64.7 2395.07    80.7 2395.35    88.7 2397.09
   104.8 2397.56   108.8 2397.37   112.8 2396.46   124.7 2391.15   128.8 2389.95
   147.9 2388.98   152.8 2388.61   162.82388.981   172.8 2389.83   180.8 2389.37
   196.8 2390.08   208.8 2392.15   216.8 2392.61   220.8 2393.73   234.5 2400.21
     241 2404.01   252.9 2411.97   265.1  2421.5   277.2 2427.59   287.2 2431.59
#Mann= 3, -1 ,  0
       0     0.1       0   147.9   0.045       0   162.8     0.1       0
#XS Ineff= 2 , 0
                          173.36         2408.43
Permanent Ineff=
       F       F
Bank Sta=147.9,162.8
XS Rating Curve= 0 ,0
Exp/Cntr(USF)=0,0
Exp/Cntr=0.3,0.1

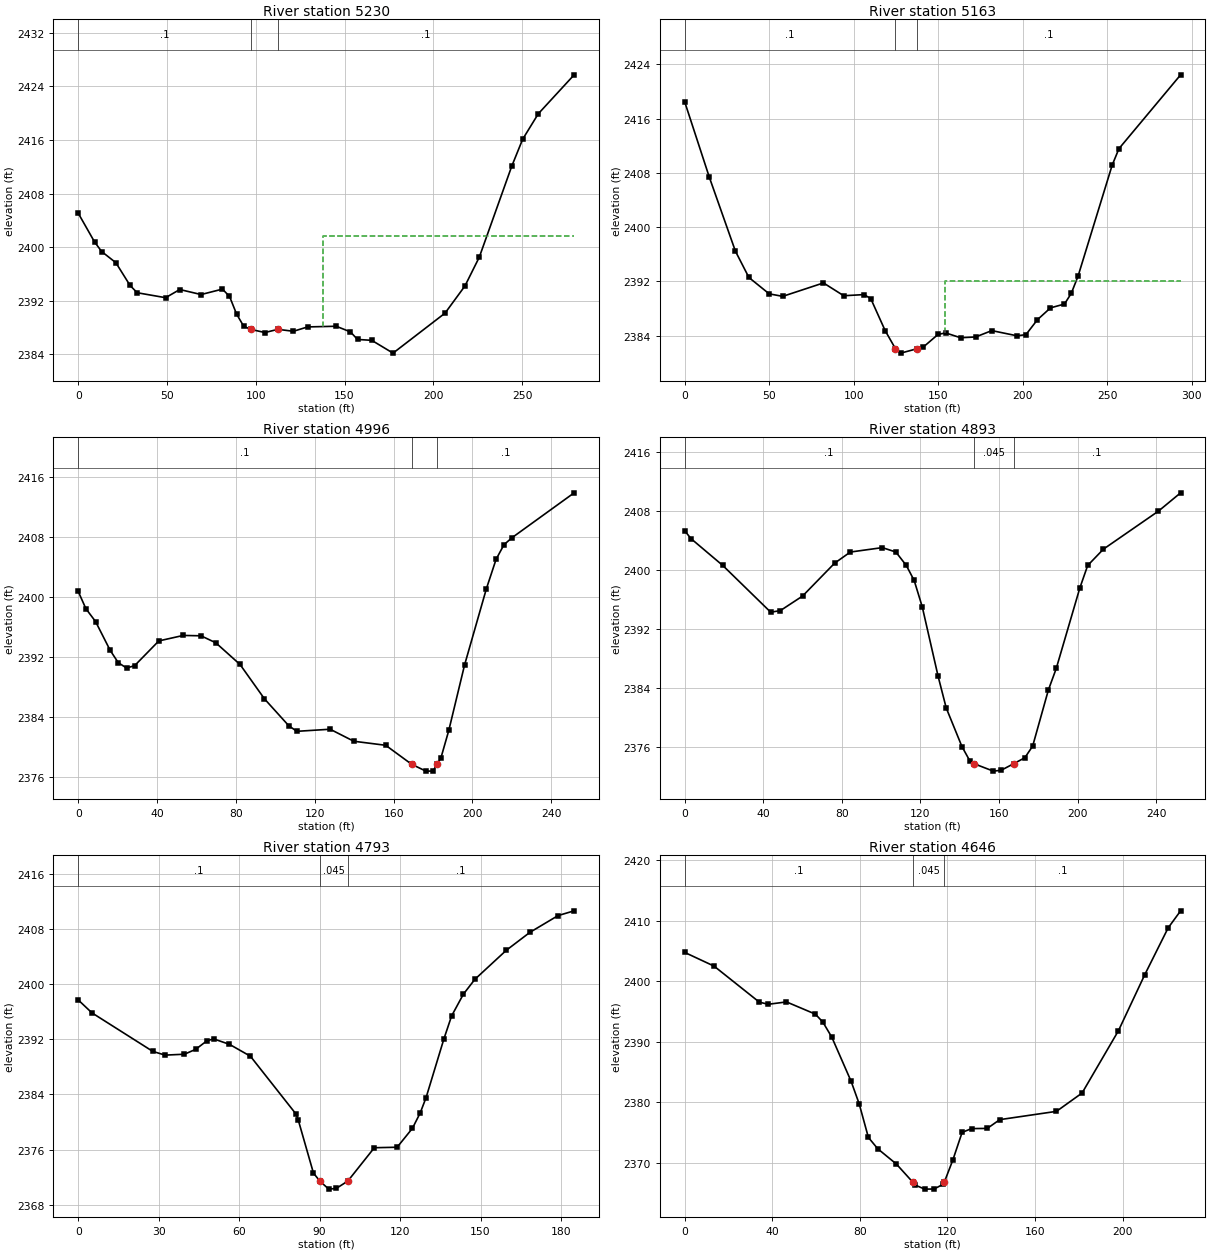
Type RM Length L Ch R = 1 ,5230    ,70.3,67.3,64.6
XS GIS Cut Line= 4
2269749.32014326615704.8592048572269658.29161694615701.224252043
 2269560.4984208615704.8774461522269471.68421066615721.559479311
#Sta/Elev= 30
       0 2405.07     9.2 2400.78    13.2 2399.35    21.2 2397.68    29.2 2394.29
    33.2  2393.2    49.2 2392.46    57.2 2393.68    69.2 2392.93    81.2 2393.74
    85.2 2392.66    89.2 2390.01    93.2  2388.2    97.2 2387.73   105.2 2387.26
   112.4 2387.74   121.2 2387.45   129.2  2388.1   145.3  2388.2   153.3 2387.36
   157.3 2386.23   165.3  2386.1   177.3 2384.19   206.6 2390.16   217.8 2394.21
   225.9 2398.52   244.1 2412.04   250.3  2416.1   259.1  2419.9   279.3 2425.71
#Mann= 3, -1 ,  0
       0     0.1       0    97.2   0.045       0   112.4     0.1       0
#XS Ineff= 2 , 0
                          137.76         2401.72
Permanent Ineff=
       F       F
Bank Sta=97.2,112.4
XS Rating Curve= 0 ,0
Exp/Cntr(USF)=0,0
Exp/Cntr=0.3,0.1

Type RM Length L Ch R = 1 ,5163    ,156.1,166.3,164.3
XS GIS Cut Line= 4
2269754.13016491615623.6860822752269643.79294586615629.963306983
 2269545.7918303615676.5187407072269471.94569571615685.666836984
#Sta/Elev= 30
       0 2418.48    14.6 2407.34      30 2396.46      38 2392.57      50 2390.16
      58 2389.79    82.1 2391.77    94.1 2389.88   106.1 2390.05   110.1 2389.45
   118.6 2384.74   124.7 2382.07   127.8 2381.42  137.392382.062   141.1  2382.3
   149.9 2384.18   154.4  2384.4   163.2 2383.69   172.1  2383.8   181.7 2384.74
   196.7 2383.97   201.9 2384.15   208.7 2386.35   216.4 2388.09   224.7 2388.66
   228.7 2390.23   232.7 2392.75   252.9 2409.13   256.9 2411.56   293.4 2422.45
#Mann= 3, -1 ,  0
       0     0.1       0   124.7   0.045       0  137.39     0.1       0
#XS Ineff= 2 , 0
                           154.1         2392.08
Permanent Ineff=
       F       F
Bank Sta=124.7,137.39
XS Rating Curve= 0 ,0
Exp/Cntr=0.3,0.1

Type RM Length L Ch R = 1 ,4996    ,102.8,102.9,103
XS GIS Cut Line= 3
2269699.93662722615526.3550518072269557.76829043615561.171787348
2269452.59273515615562.622484662
#Sta/Elev= 30
       0 2400.74     3.9 2398.44     8.8 2396.73    16.2  2392.9    20.3 2391.26
    24.5 2390.54    28.6 2390.85    40.9 2394.15    53.3 2394.88    62.3 2394.83
    69.8  2393.9    82.1 2391.01    94.5 2386.43   106.8 2382.86   110.9 2382.11
   127.8 2382.39   139.8 2380.79     156 2380.25  169.17 2377.72   176.4 2376.81
     180 2376.82  182.03 2377.72     184 2378.56     188 2382.23     196 2390.94
   207.1 2401.12     212 2405.02     216 2406.96     220 2407.88   251.6 2413.87
#Mann= 3, -1 ,  0
       0     0.1       0  169.17   0.045       0  182.03     0.1       0
Bank Sta=169.17,182.03
XS Rating Curve= 0 ,0
Exp/Cntr(USF)=0,0
Exp/Cntr=0.3,0.1

Type RM Length L Ch R = 1 ,4893    ,104.5,100.3,96.5
XS GIS Cut Line= 4
2269687.28748458615436.0467159092269554.01793272615459.116120114
2269505.80169492615458.5169890752269436.94803325615460.451697569
#Sta/Elev= 30
       0 2405.35     3.2 2404.28    19.4 2400.64    43.8 2394.31    48.7 2394.53
      60  2396.5    76.3 2400.95    84.3 2402.46   100.6 2403.06   107.5 2402.46
   112.8 2400.64   116.8 2398.61   120.9 2395.05     129 2385.61   133.1 2381.35
   141.1 2376.12   145.1 2374.19   147.1 2373.81   157.1 2372.79   161.1 2372.91
  167.53 2373.81   173.1  2374.6   177.1 2376.18   185.1 2383.78   189.1 2386.69
   201.1 2397.59   205.1 2400.64   213.1 2402.85   241.1    2408   252.4 2410.48
#Mann= 3, -1 ,  0
       0     0.1       0   147.1   0.045       0  167.53     0.1       0
Bank Sta=147.1,167.53
XS Rating Curve= 0 ,0
Exp/Cntr=0.3,0.1

Type RM Length L Ch R = 1 ,4793    ,144.9,146.8,149.7
XS GIS Cut Line= 4
2269604.63662269615314.332409377 2269534.2502397 615352.40450969
2269500.21405137615381.8513017842269448.67512871615412.221369661
#Sta/Elev= 30
       0  2397.7     5.1 2395.83    27.8 2390.24    32.4  2389.7    39.6 2389.83
    43.8 2390.54      48 2391.78    50.5 2392.05    56.4 2391.26    64.2 2389.54
    81.2 2381.16      82 2380.35    87.7 2372.61   90.072371.453    93.4 2370.28
    96.2 2370.38  100.532371.452   110.4 2376.28   118.9 2376.35   124.6 2379.09
   127.5 2381.32   129.7 2383.55   136.3    2392   139.2 2395.37   143.6 2398.53
   147.9 2400.69   159.6 2404.89   168.4 2407.49   178.9 2409.92   184.9 2410.61
#Mann= 3, -1 ,  0
       0     0.1       0   90.07   0.045       0  100.53     0.1       0
Bank Sta=90.07,100.53
XS Rating Curve= 0 ,0
Exp/Cntr(USF)=0,0
Exp/Cntr=0.3,0.1

Type RM Length L Ch R = 1 ,4646    ,120.2,124.5,130.4
XS GIS Cut Line= 4
2269541.06215378615216.8288139472269461.71994926615238.432155859
 2269399.7972998615262.225895118 2269344.5592198615317.228216475
#Sta/Elev= 30
       0 2404.77    13.4 2402.51    34.1 2396.55    38.2  2396.2    46.5 2396.59
    59.7 2394.57    63.1 2393.26    67.2 2390.76      76 2383.48    79.7 2379.75
    83.9  2374.2    88.2 2372.32    96.7  2369.8  104.072366.854   105.3 2366.33
   109.6 2365.66   113.9 2365.68   118.2 2366.49  118.622366.853   122.5  2370.5
   126.7 2375.03     131 2375.66   138.2 2375.69   143.9 2377.14   169.8 2378.51
   181.5 2381.54   198.1 2391.83   210.1 2401.07   220.8 2408.82   226.5 2411.64
#Mann= 3, -1 ,  0
       0     0.1       0  104.07   0.045       0  118.62     0.1       0
Bank Sta=104.07,118.62
XS Rating Curve= 0 ,0
Exp/Cntr=0.3,0.1

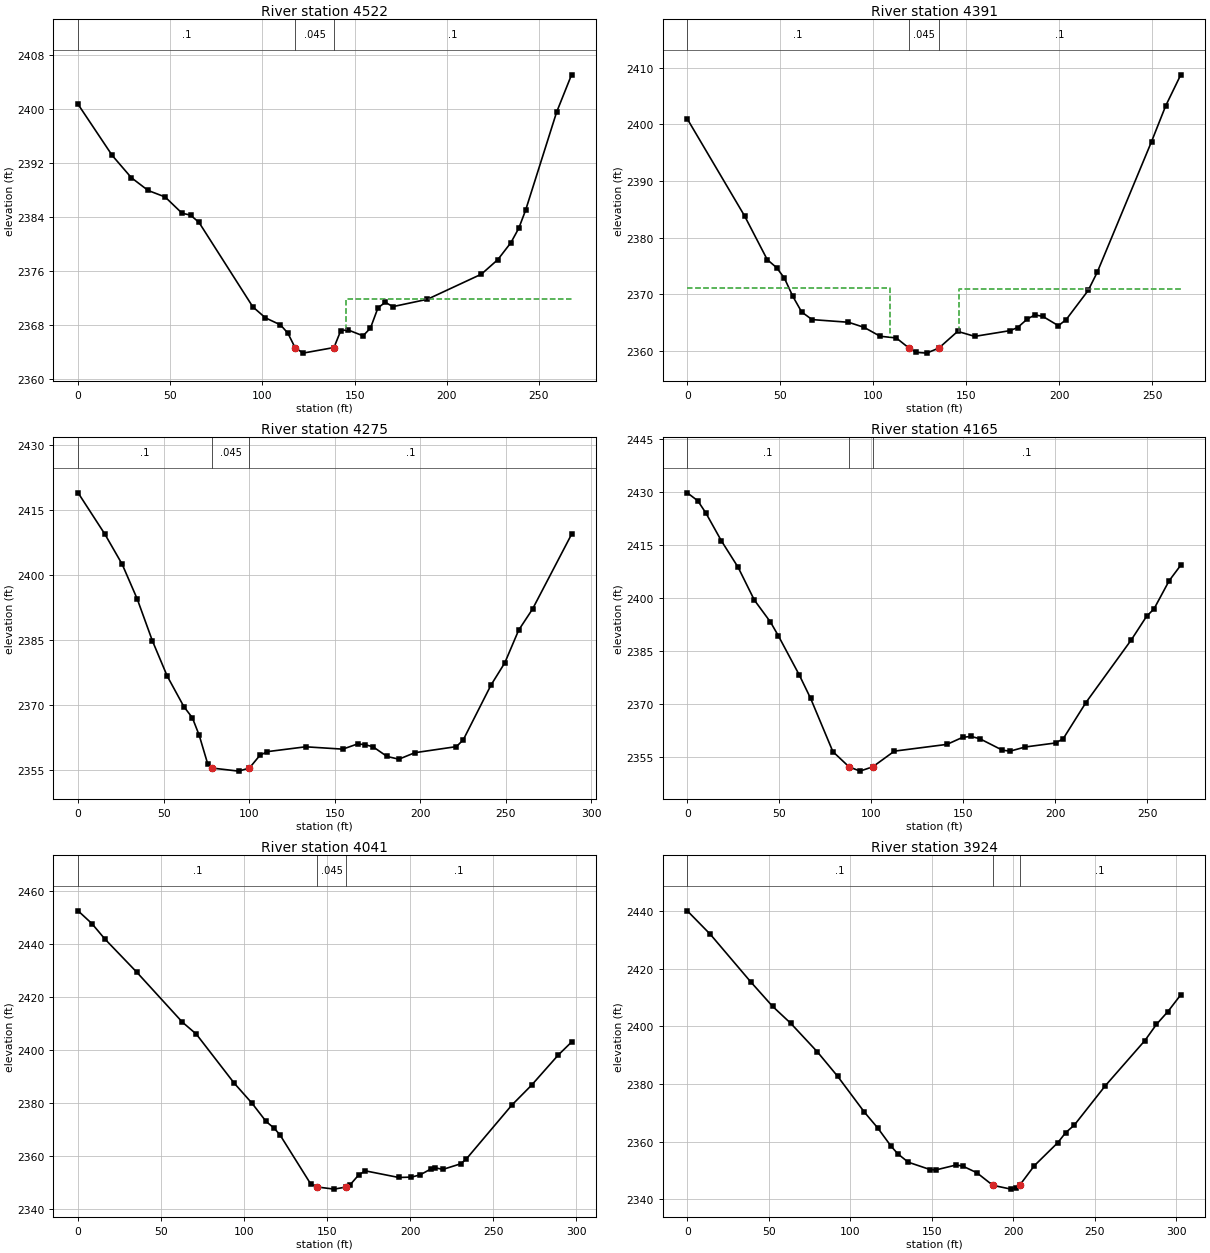
Type RM Length L Ch R = 1 ,4522    ,125.3,130.7,135.9
XS GIS Cut Line= 4
2269533.27315732615181.2778541682269450.36580581615134.275261188
2269382.47317151615121.2189853612269279.32859247 615115.99647503
#Sta/Elev= 30
       0 2400.65    18.5 2393.09    28.9 2389.79      38  2387.9    47.2 2386.94
    56.4 2384.53      61 2384.25    65.6 2383.17    94.8 2370.67   101.6 2369.05
   109.8    2368   113.8 2366.78  117.692364.647     122 2363.82  138.832364.648
   142.5 2367.15   146.4 2367.26   154.6 2366.38   158.6 2367.52   162.7 2370.53
   166.7 2371.35   170.7  2370.7   189.5 2371.79   218.8 2375.51   227.7 2377.66
   234.8 2380.17   239.1 2382.32   242.8 2384.99   259.6 2399.49   267.7 2405.02
#Mann= 3, -1 ,  0
       0     0.1       0  117.69   0.045       0  138.83     0.1       0
#XS Ineff= 2 , 0
                          145.21         2371.78
Permanent Ineff=
       F       F
Bank Sta=117.69,138.83
XS Rating Curve= 0 ,0
Exp/Cntr(USF)=0,0
Exp/Cntr=0.3,0.1

Type RM Length L Ch R = 1 ,4391    ,118.4,115.9,110.8
XS GIS Cut Line= 4
2269576.38611348615081.4175740222269521.45367555615058.074888988
2269437.19169693614975.5703325662269353.16648082614950.112206921
#Sta/Elev= 30
       0 2400.95    30.8 2383.83      43 2376.11      48  2374.7    52.2 2372.86
    56.7 2369.66    61.5 2366.87    67.1 2365.52    86.7 2365.05    95.1 2364.15
   103.7 2362.58   112.4 2362.28  119.25 2360.49   123.1 2359.74   128.7  2359.6
   135.3 2360.49   145.4 2363.44   154.6 2362.56   173.4 2363.56   177.6  2364.1
   182.9 2365.63     187 2366.35   191.2 2366.09   199.6 2364.44   203.8 2365.53
   215.6 2370.66   220.5 2373.89   249.7 2396.96   257.3 2403.26   265.4 2408.74
#Mann= 3, -1 ,  0
       0     0.1       0  119.25   0.045       0   135.3     0.1       0
#XS Ineff= 2 , 0
          109.25  2371.1  145.87         2371.01
Permanent Ineff=
       F       F
Bank Sta=119.25,135.3
XS Rating Curve= 0 ,0
Exp/Cntr=0.3,0.1

Type RM Length L Ch R = 1 ,4275    ,117.5,110.5,98.2
XS GIS Cut Line= 4
2269633.81257054614974.7097999782269572.42130879614939.493107188
2269478.51809857614896.2372182012269365.67941135614914.238541484
#Sta/Elev= 30
       0 2418.91    15.7 2409.37    25.8 2402.44    34.6 2394.44    43.4 2384.87
    52.1 2376.72    61.8 2369.71    66.8 2367.12    70.8 2363.09    75.7 2356.59
   78.442355.552    93.8 2354.85   100.12355.554   106.3  2358.5   110.7 2359.34
     133 2360.45   154.7 2359.91   163.5 2361.13   167.9 2360.91   172.3 2360.47
   180.6 2358.22   187.5  2357.6   196.8 2359.09   221.1 2360.49   225.1 2362.04
   241.3 2374.64   249.4 2379.78   257.5  2387.3   265.6 2392.15   288.4 2409.35
#Mann= 3, -1 ,  0
       0     0.1       0   78.44   0.045       0   100.1     0.1       0
Bank Sta=78.44,100.1
XS Rating Curve= 0 ,0
Exp/Cntr(USF)=0,0
Exp/Cntr=0.3,0.1

Type RM Length L Ch R = 1 ,4165    ,128.7,123.6,120.6
XS GIS Cut Line= 4
2269613.40603931614793.9416988252269537.70171515 614827.73534088
2269471.40175323614866.585502192 2269366.1053047614892.052757366
#Sta/Elev= 30
       0 2429.85     5.7 2427.59    10.1 2424.12    18.5 2416.24    27.6 2408.73
    36.4 2399.44    45.2 2393.18    49.5 2389.26    60.9 2378.11      67 2371.53
    79.1 2356.42   87.862352.116    93.8 2350.89  100.782352.117   112.5 2356.56
   141.1 2358.48   149.6 2360.48   154.2 2360.73   158.9 2360.09   171.2 2356.83
   175.4 2356.56   183.6 2357.74   200.1 2358.88   204.2 2360.05   216.6 2370.36
   241.3 2388.18   249.5 2394.78   253.6 2396.94   261.8 2404.91   268.1 2409.31
#Mann= 3, -1 ,  0
       0     0.1       0   87.86   0.045       0  100.78     0.1       0
Bank Sta=87.86,100.78
XS Rating Curve= 0 ,0
Exp/Cntr=0.3,0.1

Type RM Length L Ch R = 1 ,4041    ,115.8,117.6,118.4
XS GIS Cut Line= 4
2269592.06373798  614680.81307982269462.15379349614721.940348657
 2269427.1666803614778.2875859012269344.94379295614825.123407805
#Sta/Elev= 30
       0 2452.51     8.3  2447.7    16.1  2441.9    35.3 2429.38    62.8  2410.5
    71.2 2405.98      94 2387.49   104.8 2379.86   113.2 2373.04   118.1 2370.47
   121.6 2367.95   140.1 2349.43  143.992348.292   154.2 2347.48  161.612348.293
   163.6 2348.94   169.1  2352.9     173 2354.38   193.1 2351.88   200.7 2352.01
     206 2352.86   212.8 2355.19   215.2 2355.49   219.8 2354.94   230.4 2357.03
   233.7 2358.76   261.3 2379.23   273.1 2386.69   289.2 2398.09   297.2 2402.98
#Mann= 3, -1 ,  0
       0     0.1       0  143.99   0.045       0  161.61     0.1       0
Bank Sta=143.99,161.61
XS Rating Curve= 0 ,0
Exp/Cntr(USF)=0,0
Exp/Cntr=0.3,0.1

Type RM Length L Ch R = 1 ,3924    ,133.1,137.3,139.1
XS GIS Cut Line= 4
 2269525.9493696614592.0125097952269397.82305443614622.165475101
2269347.87700767614680.6772003972269269.68920689614733.531134939
#Sta/Elev= 30
       0    2440    14.2 2431.81      39 2415.33    52.3 2406.92    63.5 2401.01
    79.9 2391.07    92.2  2382.7   108.7 2370.22   116.9 2364.73   125.1  2358.4
   129.2 2355.78   135.6 2352.87   149.1  2350.3   152.6 2350.19     165 2351.89
     169 2351.53   177.7 2349.22  187.562344.851   198.7 2343.53   201.9 2343.99
     204 2344.85     213 2351.64   227.5 2359.68   232.3 2363.14   237.5 2365.68
   256.5  2379.3   280.9 2395.04     288 2400.65     295 2405.07   302.9 2410.88
#Mann= 3, -1 ,  0
       0     0.1       0  187.56   0.045       0     204     0.1       0
Bank Sta=187.56,204
XS Rating Curve= 0 ,0
Exp/Cntr=0.3,0.1