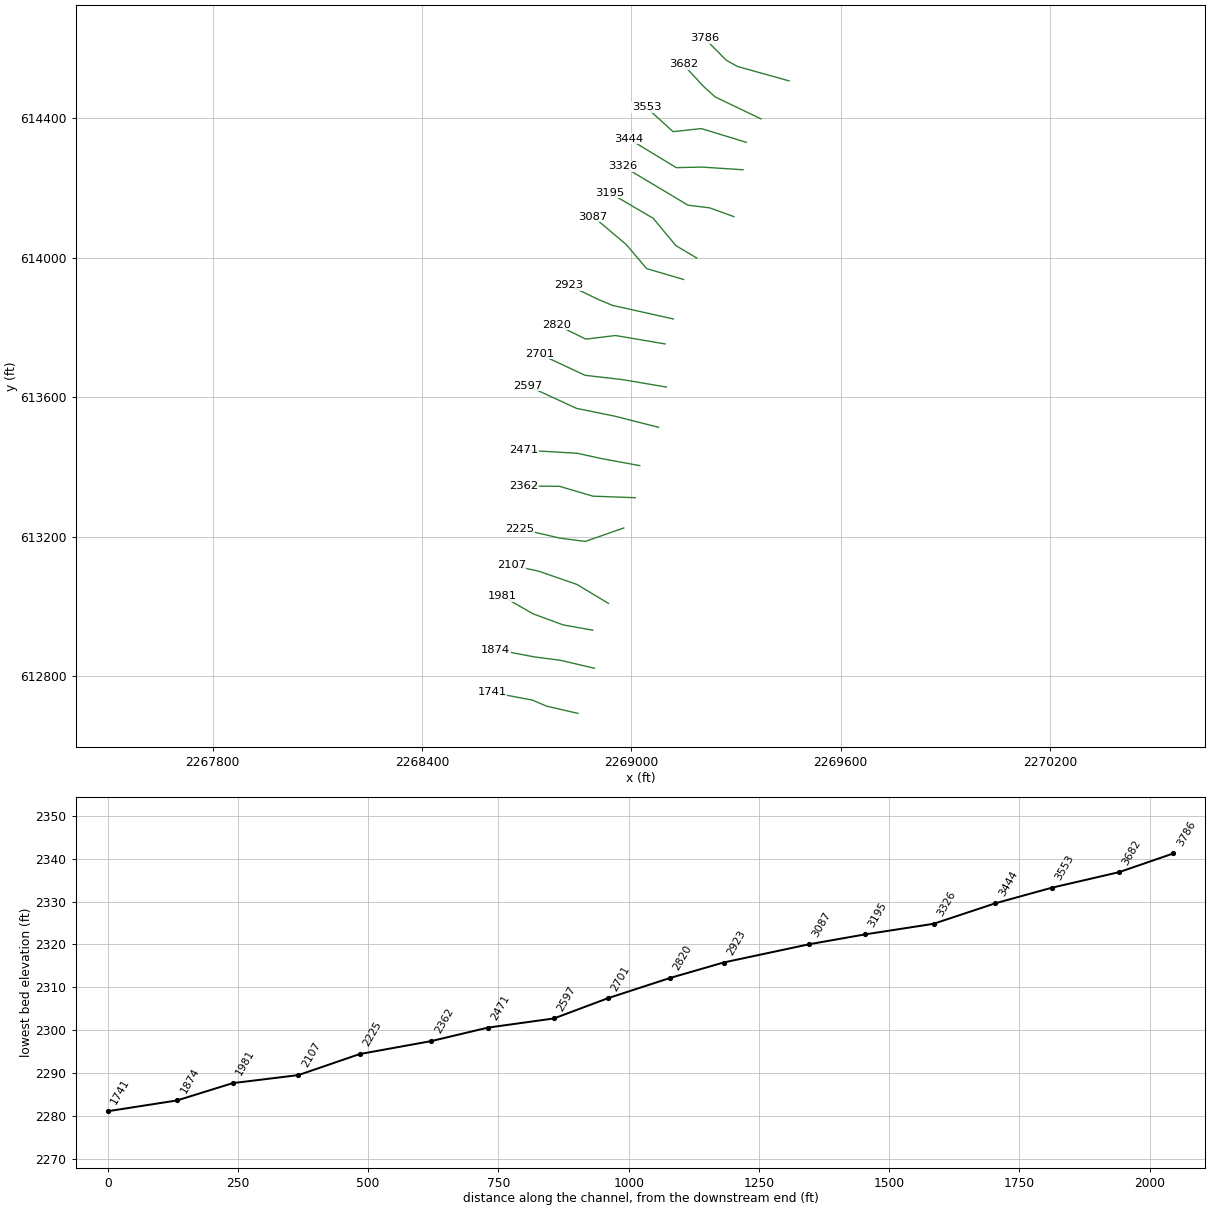
HEC-RAS study LAURELRN5.prj: LAURELRN5

--- LAURELRN5.g01 (geometry) --- (continued)

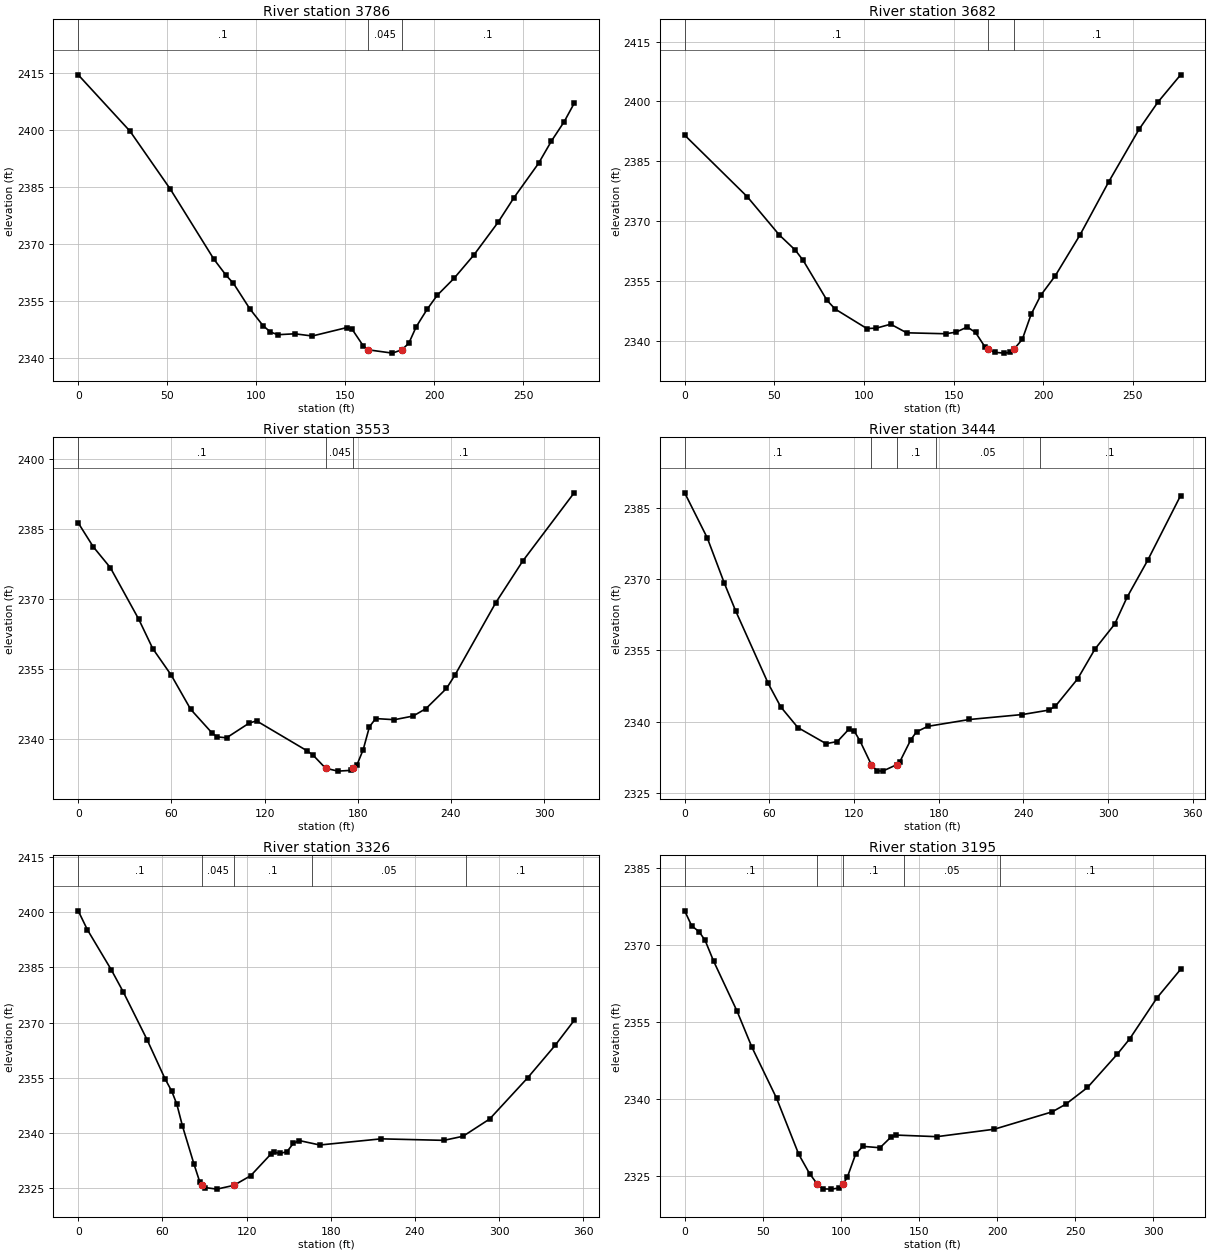
Type RM Length L Ch R = 1 ,3786    ,106.7,104.3,102.1
XS GIS Cut Line= 4
2269452.19887277614507.2803773292269304.66295592614548.407646186
2269272.50452216614566.088126939 2269210.0854876614629.209120544
#Sta/Elev= 30
       0  2414.5    29.1 2399.66    51.8 2384.36    76.2 2365.97    83.1 2361.69
    87.2  2359.6    96.4 2352.89   103.8 2348.47     108 2346.78   112.1 2346.07
   121.7 2346.31   131.5 2345.73   150.9 2347.95   153.7 2347.62     160 2343.22
  162.692342.106   176.5 2341.22  181.792342.104   185.7 2343.81   189.9 2348.18
     196 2352.76   201.7 2356.46   211.1  2360.9   222.3 2367.08   235.8 2375.63
   244.8 2382.16   258.6 2391.19   265.8 2397.04     273 2402.16   278.6 2406.99
#Mann= 3, -1 ,  0
       0     0.1       0  162.69   0.045       0  181.79     0.1       0
Bank Sta=162.69,181.79
XS Rating Curve= 0 ,0
Exp/Cntr(USF)=0,0
Exp/Cntr=0.3,0.1

Type RM Length L Ch R = 1 ,3682    ,121.2,128.9,135
XS GIS Cut Line= 4
2269371.81597528614398.2925440942269240.52309136614461.133139302
2269207.44427288614490.9070212732269148.77964697 614554.46033568
#Sta/Elev= 30
       0 2391.55    34.9  2376.1    52.8 2366.49    61.7  2362.7    66.1 2360.11
    79.4 2350.09    83.9 2347.92   101.6 2343.02   106.9 2343.12   114.9 2344.11
   123.8 2341.95   145.6 2341.71   151.4 2342.12   157.6  2343.4   162.2 2342.05
   167.6 2338.33  169.362337.771   172.9 2337.05   178.3 2336.85   181.5 2337.03
  183.492337.771   188.3  2340.3   193.2 2346.56   198.6 2351.37   206.7 2356.27
   220.4 2366.44   236.4 2379.76   253.4    2393   263.9 2399.82   276.6 2406.69
#Mann= 3, -1 ,  0
       0     0.1       0  169.36   0.045       0  183.49     0.1       0
Bank Sta=169.36,183.49
XS Rating Curve= 0 ,0
Exp/Cntr=0.3,0.1

Type RM Length L Ch R = 1 ,3553    ,109.2,108.7,107.7
XS GIS Cut Line= 4
2269329.43429981 614331.124763542269200.76470152614370.489435161
2269119.68522863614361.6764489772269043.30601504614431.005273623
#Sta/Elev= 30
       0 2386.28     9.7 2381.16    20.7  2376.7      39 2365.67      48 2359.41
    59.9 2353.74    72.4 2346.44    85.9 2341.48    89.2 2340.56    95.5 2340.35
   110.1  2343.5   114.8 2343.97   147.2  2337.6   151.2 2336.65   159.3 2333.84
   167.3 2333.23   175.4 2333.39  177.13 2333.81   179.4  2334.5   183.5 2337.84
   187.5 2342.71   191.5 2344.46   203.6 2344.22   215.6    2345   223.9 2346.59
   237.1  2350.9   242.5 2353.72   268.9 2369.26   286.2 2378.12   319.3  2392.7
#Mann= 3, -1 ,  0
       0     0.1       0   159.3   0.045       0  177.13     0.1       0
Bank Sta=159.3,177.13
XS Rating Curve= 0 ,0
Exp/Cntr(USF)=0,0
Exp/Cntr=0.3,0.1

Type RM Length L Ch R = 1 ,3444    ,119.7,118.6,115.2
XS GIS Cut Line= 4
2269320.17969089614252.4424876872269202.47081378614260.082722219
2269128.90189015614258.4963847062268992.27401604614341.460289266
#Sta/Elev= 30
       0 2388.17      16 2378.69    28.1 2369.15    36.1 2363.33    59.2 2348.04
    68.1  2343.1    80.2 2338.76   100.2 2335.37   108.2 2335.82   116.2 2338.37
   120.3 2337.94   124.3  2335.9   132.3 2330.92   136.3 2329.66   140.3 2329.59
  150.11 2330.93   152.3 2331.48   160.3 2336.24   164.3 2337.87   172.3 2339.02
   201.8 2340.46   239.2  2341.5   257.9 2342.43   262.6 2343.23   278.5 2349.04
   290.7 2355.28   304.7 2360.54   313.4 2366.16     328 2373.93   351.4  2387.6
#Mann= 5, -1 ,  0
       0     0.1       0   132.3   0.045       0  150.11     0.1       0
  177.96    0.05       0  251.54     0.1       0
Bank Sta=132.3,150.11
XS Rating Curve= 0 ,0
Exp/Cntr=0.3,0.1

Type RM Length L Ch R = 1 ,3326    ,138.1,131.1,121.4
XS GIS Cut Line= 4
2269294.33258141614117.9695738242269224.41622435614143.233467551
2269162.54906134614150.8478876142268976.47167106614262.208781033
#Sta/Elev= 30
       0  2400.3     6.5  2395.2    23.6 2384.29    32.1 2378.31    49.1 2365.34
    61.8 2354.81    66.7 2351.34    70.3 2347.84    74.3 2341.94    82.6  2331.5
    86.7 2326.69   88.13 2325.87    90.7 2325.22    98.8 2324.81   110.9 2325.83
   122.9 2328.44   137.2 2334.26   139.4 2334.83   144.1  2334.5   148.8 2334.98
   153.4 2337.24   157.6 2337.98   172.2 2336.78   215.9 2338.45   260.6 2338.04
   274.3 2339.15   293.3 2343.84   320.4 2355.02   339.9 2363.79   353.5 2370.57
#Mann= 5, -1 ,  0
       0     0.1       0   88.13   0.045       0   110.9     0.1       0
  166.67    0.05       0  276.67     0.1       0
Bank Sta=88.13,110.9
XS Rating Curve= 0 ,0
Exp/Cntr(USF)=0,0
Exp/Cntr=0.3,0.1

Type RM Length L Ch R = 1 ,3195    ,107.2,107.5,107.4
XS GIS Cut Line= 4
2269188.05069899613999.1456356072269127.65885438614035.027875255
2269062.62212568614113.4020466462268937.17049031614186.813948306
#Sta/Elev= 30
       0 2376.62     4.5 2373.68     9.2 2372.57    13.1 2370.84    18.5 2366.82
    33.5 2357.07    43.1 2349.98    58.8 2340.08      73 2329.14    79.9 2325.39
   84.992323.285    88.6  2322.4    93.8 2322.35      99 2322.57  101.352323.284
   104.2 2324.77   109.4 2329.16     114 2330.69     125 2330.42   132.1 2332.52
   135.4 2332.89   161.4 2332.58   198.1 2334.03   235.2 2337.42   243.9 2338.91
   257.8 2342.17   276.9 2348.68   284.8 2351.65   302.4  2359.7   317.4 2365.21
#Mann= 5, -1 ,  0
       0     0.1       0   84.99   0.045       0  101.35     0.1       0
  140.25    0.05       0  202.09     0.1       0
Bank Sta=84.99,101.35
XS Rating Curve= 0 ,0
Exp/Cntr=0.3,0.1

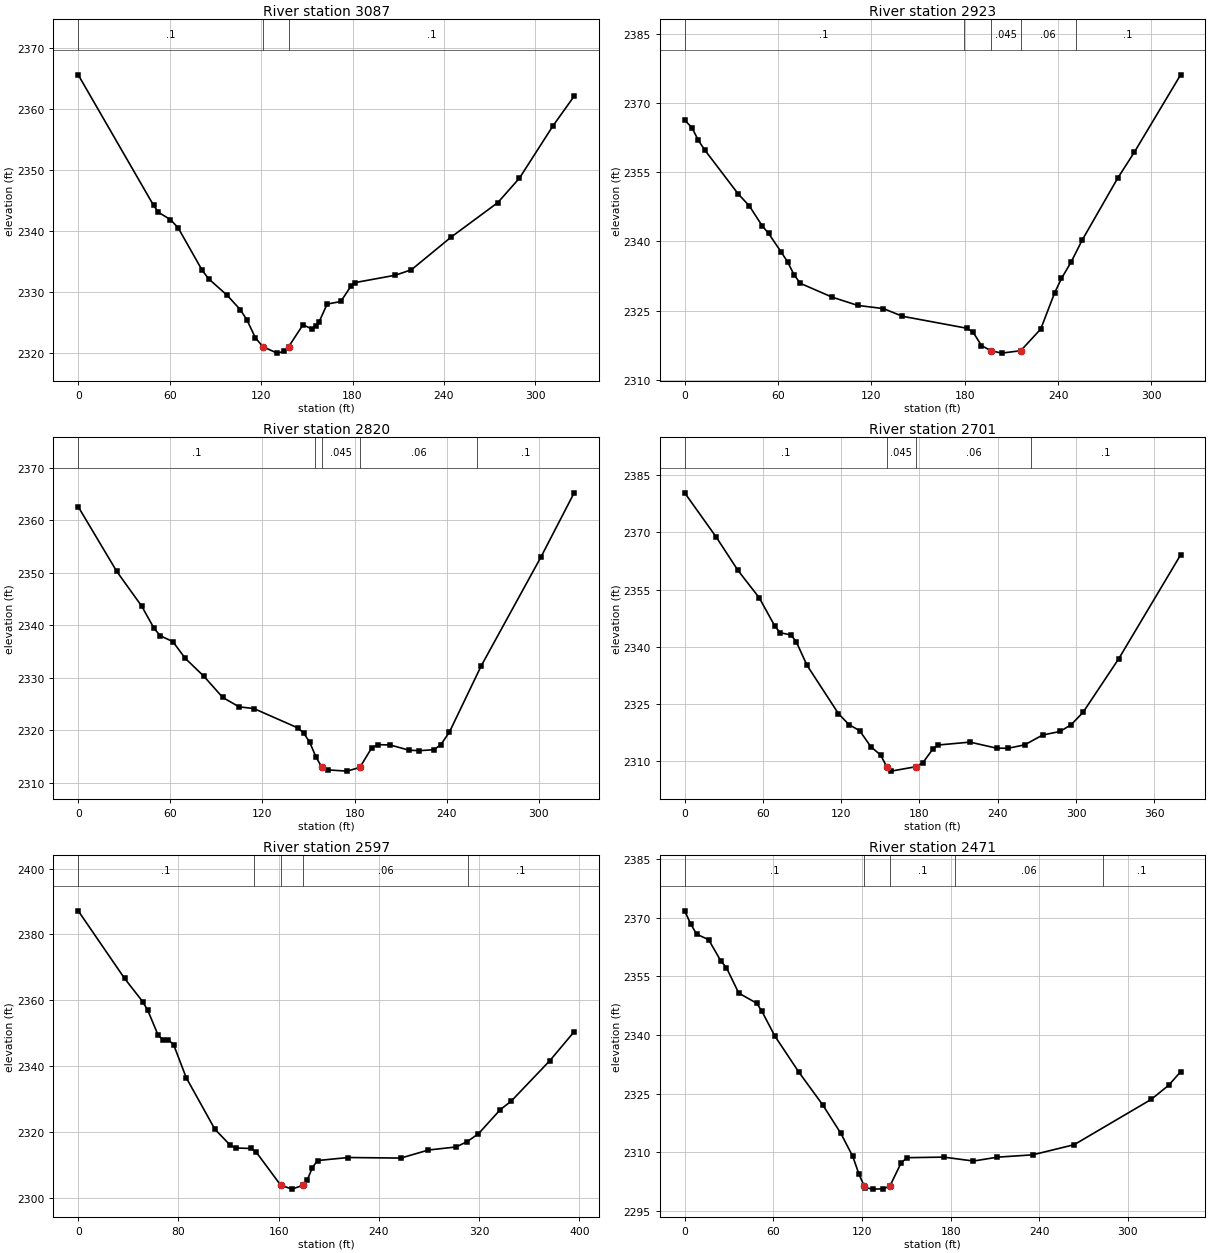
Type RM Length L Ch R = 1 ,3087    ,158.4,164.4,167.3
XS GIS Cut Line= 4
2269150.18185563613937.8614255022269043.89724225613969.059396592
2268985.73153344614037.8006888262268890.55128266614118.175122822
#Sta/Elev= 30
       0 2365.59    49.4 2344.25    52.6  2343.1    60.5  2341.9    65.5 2340.58
    81.3 2333.62    85.5 2332.23    97.8  2329.5   106.3 2327.17   110.6 2325.53
   116.3 2322.53  121.232321.096   130.5 2320.05   135.1 2320.34  138.062321.096
   147.5  2324.7   153.2    2324   156.1 2324.49   158.1 2325.19   163.3 2328.07
   172.3  2328.5     179 2331.03   181.6 2331.59   208.1  2332.8   218.6 2333.69
   244.7 2339.04   275.3 2344.68   289.5 2348.68   311.4  2357.2   325.4  2362.1
#Mann= 3, -1 ,  0
       0     0.1       0  121.23   0.045       0  138.06     0.1       0
Bank Sta=121.23,138.06
XS Rating Curve= 0 ,0
Exp/Cntr(USF)=0,0
Exp/Cntr=0.3,0.1

Type RM Length L Ch R = 1 ,2923    ,96.5,103.2,106.6
XS GIS Cut Line= 4
2269120.75521485613824.6253997582268945.70490836613863.766702685
2268906.97648437613879.951603194  2268819.082814613922.067589009
#Sta/Elev= 30
       0 2366.32     4.7 2364.64     8.8  2361.9    12.9 2359.83    34.4  2350.3
    41.6 2347.69    49.8 2343.39    53.9 2341.76    62.1 2337.67    66.2 2335.55
    70.3 2332.77    74.4 2330.91    94.9 2327.91   111.3 2326.13   127.7 2325.45
     140 2323.78   181.6 2321.17   185.4 2320.32   190.8 2317.43   196.72316.328
   203.8 2315.79  216.04 2316.32   228.9 2321.02   237.8 2328.85   242.2 2331.97
   248.4 2335.53   255.5 2340.28   278.3 2353.69     289 2359.32   318.8 2376.12
#Mann= 5, -1 ,  0
       0     0.1       0  179.37    0.06       0   196.7   0.045       0
  216.04    0.06       0  251.35     0.1       0
Bank Sta=196.7,216.04
XS Rating Curve= 0 ,0
Exp/Cntr=0.3,0.1

Type RM Length L Ch R = 1 ,2820    ,122,118.7,116.7
XS GIS Cut Line= 4
2269096.91510276613753.0799580662268954.60169624613777.234068348
2268869.73590336613766.7890476862268786.17573806613807.916316543
#Sta/Elev= 30
       0 2362.61    25.1 2350.27    41.3 2343.66    49.4 2339.41    53.5 2337.98
    61.6 2336.89    69.7 2333.69    81.9 2330.25    94.1 2326.23   104.8 2324.43
   114.4 2324.11   142.9 2320.43   146.8 2319.46   150.8 2317.66   154.9 2314.83
  158.772312.867   162.9  2312.4     175 2312.17   183.42312.867   191.1 2316.58
   195.2 2317.22   203.2 2317.16   215.3 2316.17   221.9 2316.07   231.6 2316.25
   236.1 2317.19   241.8 2319.64   262.4 2332.21   301.5 2353.08     323 2365.26
#Mann= 5, -1 ,  0
       0     0.1       0  154.35    0.06       0  158.77   0.045       0
   183.4    0.06       0  259.85     0.1       0
Bank Sta=158.77,183.4
XS Rating Curve= 0 ,0
Exp/Cntr(USF)=0,0
Exp/Cntr=0.3,0.1

Type RM Length L Ch R = 1 ,2701    ,105.1,103.7,102.9
XS GIS Cut Line= 4
2269100.44751638 613629.48060341 2268976.2866262613650.548984284
2268867.40668061613663.1482633492268736.37211007613724.479340057
#Sta/Elev= 30
       0  2380.3    24.3 2368.66    40.8 2360.02    57.1 2352.86    69.3 2345.32
    73.3 2343.68    81.4 2343.12    85.5 2341.36    93.8 2335.15   117.9 2322.51
   125.9 2319.65   134.1 2318.07   142.8 2313.83   150.2 2311.69  154.922308.615
   158.3 2307.47  177.062308.614   182.4 2309.59   190.5 2313.35   194.5 2314.31
   218.7 2315.06   239.1 2313.48   247.9 2313.45   260.6 2314.34   274.4 2316.91
   287.7 2317.85   296.2 2319.59   305.4 2322.85   332.8  2336.9   380.2 2364.06
#Mann= 4, -1 ,  0
       0     0.1       0  154.92   0.045       0  177.06    0.06       0
  265.54     0.1       0
Bank Sta=154.92,177.06
XS Rating Curve= 0 ,0
Exp/Cntr=0.3,0.1

Type RM Length L Ch R = 1 ,2597    ,127.1,126.5,126.9
XS GIS Cut Line= 4
2269077.96466164 613514.15382575 2268951.9715999613546.141701529
2268842.95169674613568.3373704362268702.59673159613632.965935784
#Sta/Elev= 30
       0 2387.17      37 2366.66    51.4 2359.65    55.5 2356.98    63.8 2349.44
    67.9 2347.94      72 2347.99    76.1 2346.61    86.2 2336.56   109.1  2320.9
   121.5 2316.01   125.7 2315.23   137.9 2315.08     142    2314  161.582303.955
   170.6 2302.75  179.562303.954   182.8 2305.51   186.9 2309.29     191 2311.42
   215.5 2312.34   257.5 2312.17   279.5 2314.61   301.6 2315.54   310.4 2317.16
   319.4 2319.53   336.8 2326.84   345.6 2329.45   376.4 2341.72   395.8  2350.5
#Mann= 5, -1 ,  0
       0     0.1       0  139.99    0.06       0  161.58   0.045       0
  179.56    0.06       0  311.25     0.1       0
Bank Sta=161.58,179.56
XS Rating Curve= 0 ,0
Exp/Cntr(USF)=0,0
Exp/Cntr=0.3,0.1

Type RM Length L Ch R = 1 ,2471    ,109.6,108.7,108.4
XS GIS Cut Line= 4
2269024.12136602613404.2032765482268910.39006673613425.254680002
2268844.74364469613439.6955966922268692.16665704613448.601528879
#Sta/Elev= 30
       0 2371.75       4 2368.44     8.1 2365.77    16.2 2364.38    24.4 2358.99
    28.3 2357.19    36.6 2350.72    48.8 2348.12    52.3 2346.05      61 2339.77
    77.2 2330.57    93.5 2322.12   105.7 2314.88   113.8 2308.96   117.9 2304.52
  121.562301.348     122    2301   127.5 2300.62   134.2 2300.69  138.832301.348
   146.6  2307.4   150.7 2308.66   175.3  2308.8   195.5  2307.8   211.7 2308.79
   235.5 2309.38   263.6 2311.97   315.7 2323.53   327.7 2327.19   335.7 2330.63
#Mann= 5, -1 ,  0
       0     0.1       0  121.56   0.045       0  138.83     0.1       0
  182.88    0.06       0  282.88     0.1       0
Bank Sta=121.56,138.83
XS Rating Curve= 0 ,0
Exp/Cntr=0.3,0.1

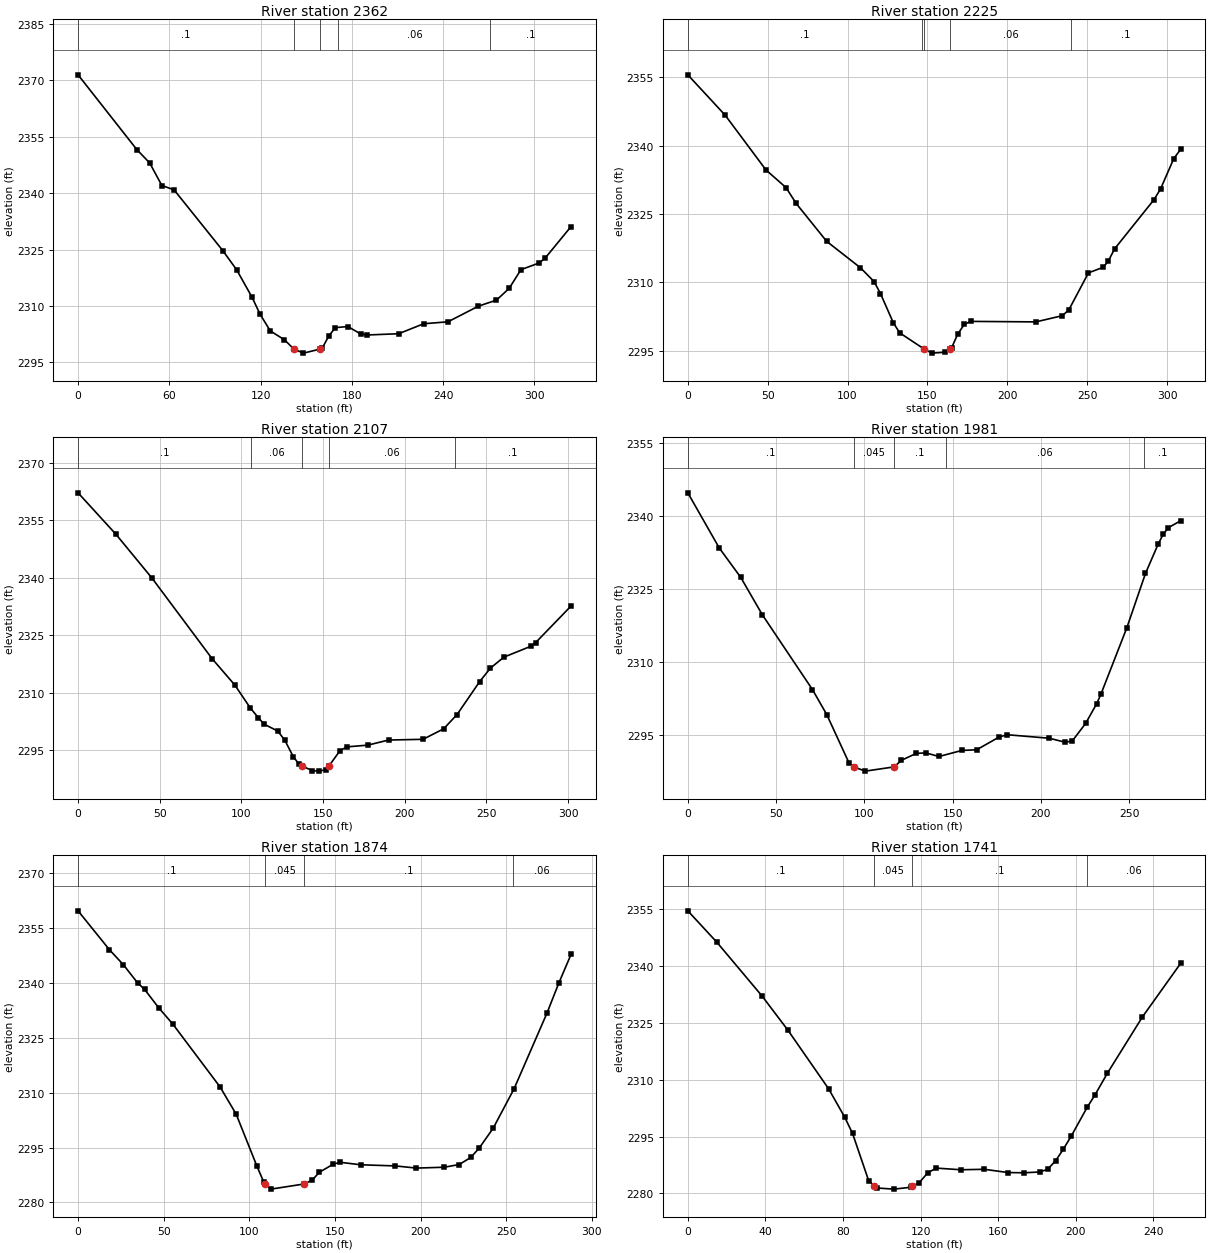
Type RM Length L Ch R = 1 ,2362    ,136.4,137.3,138.9
XS GIS Cut Line= 4
  2269011.205659613312.2600818612268890.07243327613316.612173804
2268794.32641053613344.9007714312268691.32690122613345.626120088
#Sta/Elev= 30
       0 2371.49    38.6 2351.63    47.1 2348.05    55.1 2342.05    63.1 2340.91
    95.1 2324.77   104.3 2319.62   114.3  2312.4   119.7  2307.8   126.4 2303.38
   135.7 2301.03  141.912298.551   148.2 2297.48  159.112298.552   160.7 2298.95
   164.9 2302.06   169.1 2304.26   177.4 2304.55   185.8 2302.58   189.9  2302.3
   210.8 2302.64   227.2 2305.29   243.2 2305.81   263.2 2309.97   275.1 2311.58
   283.4 2314.69   291.2 2319.68   303.2 2321.46   307.2  2322.8   324.1 2331.13
#Mann= 5, -1 ,  0
       0     0.1       0  141.91   0.045       0  159.11     0.1       0
  171.21    0.06       0  271.05     0.1       0
Bank Sta=141.91,159.11
XS Rating Curve= 0 ,0
Exp/Cntr(USF)=0,0
Exp/Cntr=0.3,0.1

Type RM Length L Ch R = 1 ,2225    ,119.5,117.9,116.1
XS GIS Cut Line= 4
2268978.27610165613225.3870026942268867.95273562613186.941529097
2268795.32254196613196.3420435132268679.88272762613223.306278522
#Sta/Elev= 30
       0 2355.58    23.4 2346.71    48.9  2334.7    61.5 2330.81    67.8 2327.35
    86.9 2319.02   108.1  2313.2   116.6 2310.17   120.6 2307.55   128.7 2301.09
   132.7  2298.9  147.97 2295.35   152.9 2294.46     161 2294.66  164.072295.351
   165.1 2295.59     169 2298.66   173.1 2300.77   177.1 2301.43   217.9 2301.32
   234.4 2302.68   238.5 2303.94   250.8 2312.09     260 2313.31   263.1 2314.59
   267.2 2317.37   291.9 2328.19     296 2330.56   304.2 2337.17   308.6 2339.26
#Mann= 5, -1 ,  0
       0     0.1       0  146.83    0.06       0  147.97   0.045       0
  164.07    0.06       0  240.07     0.1       0
Bank Sta=147.97,164.07
XS Rating Curve= 0 ,0
Exp/Cntr=0.3,0.1

Type RM Length L Ch R = 1 ,2107    ,126.3,125.9,124.5
XS GIS Cut Line= 4
2268934.51203961613009.2674464022268843.84345747613063.668595685
2268735.04115891613101.3867258542268655.97815528613118.795093625
#Sta/Elev= 30
       0 2362.14    23.2 2351.32    45.4 2339.82      82 2318.91      96 2311.99
   105.4 2306.06   110.3 2303.51   113.9  2301.8   122.3 2299.99   126.6 2297.59
   131.8 2293.29     135 2291.53   137.12290.886   143.5 2289.67   147.7 2289.55
     152 2289.97   153.62290.887   160.4 2294.91   164.7 2295.88   177.4 2296.33
   190.1 2297.66   211.2 2297.85   223.8 2300.58     232 2304.29   245.9 2312.92
   252.5 2316.44   260.7 2319.28   277.1  2322.1   280.2  2323.1   301.8 2332.61
#Mann= 5, -1 ,  0
       0     0.1       0  105.74    0.06       0   137.1   0.045       0
   153.6    0.06       0  230.89     0.1       0
Bank Sta=137.1,153.6
XS Rating Curve= 0 ,0
Exp/Cntr(USF)=0,0
Exp/Cntr=0.3,0.1

Type RM Length L Ch R = 1 ,1981    ,104.2,107.1,109.4
XS GIS Cut Line= 4
2268889.69301687612932.3572249012268804.73235005612947.518286945
2268718.44174434612979.2591629732268630.83277747613029.411927508
#Sta/Elev= 30
       0 2344.72    17.8 2333.42      30 2327.38    42.2 2319.73    70.6 2304.39
    78.7 2299.27    91.2 2289.44      942288.546   100.5 2287.68  116.822288.547
     121  2289.9   129.5 2291.33   134.8 2291.41   142.3 2290.68   155.1 2291.91
   163.6 2292.06   176.4 2294.68   180.9 2295.14   204.8 2294.42   213.6 2293.61
   217.7 2293.84   225.3 2297.45   231.6 2301.51   234.1 2303.56   248.7 2317.11
   259.2 2328.19   266.3 2334.13   269.2  2336.2   272.2 2337.58   279.2 2339.02
#Mann= 5, -1 ,  0
       0     0.1       0      94   0.045       0  116.82     0.1       0
   146.3    0.06       0  258.25     0.1       0
Bank Sta=94,116.82
XS Rating Curve= 0 ,0
Exp/Cntr=0.3,0.1

Type RM Length L Ch R = 1 ,1874    ,135.7,133,129.9
XS GIS Cut Line= 4
2268893.98996188612823.3356395392268796.45958145612846.249403617
2268723.42213471612855.5940478812268611.38687159612876.801089055
#Sta/Elev= 30
       0 2359.67    18.3 2349.05    26.5 2344.92    34.7 2340.02    38.8 2338.23
    47.1 2333.17    55.3 2328.74    82.9 2311.56    92.3 2304.12   104.5 2289.83
   108.5 2285.47  109.382285.056   112.6 2283.64  132.082285.055   136.8 2286.14
   140.8 2288.23   148.9 2290.43   152.9 2290.98     165 2290.29   185.3 2289.98
   197.5 2289.39   213.8 2289.62   222.5 2290.36   229.3  2292.3   234.1  2294.8
   242.3 2300.24   254.5    2311   273.8 2331.77   280.6 2339.85   287.8 2347.75
#Mann= 4, -1 ,  0
       0     0.1       0  109.38   0.045       0  132.08     0.1       0
  253.82    0.06       0
Bank Sta=109.38,132.08
XS Rating Curve= 0 ,0
Exp/Cntr(USF)=0,0
Exp/Cntr=0.3,0.1

Type RM Length L Ch R = 1 ,1741    ,118.4,119.1,120
XS GIS Cut Line= 4
2268846.90097537612693.9377583032268757.12907702612714.645391822
2268716.91886197 612731.860005882268600.73485399 612753.90448308
#Sta/Elev= 30
       0 2354.53      15 2346.23    38.3 2332.04    51.7 2322.98    72.6 2307.57
    80.8 2300.18    84.9 2295.84    93.2 2283.39   96.182281.963    97.5 2281.43
   106.2 2281.13   114.9 2281.62  115.762281.964   119.2 2282.78   123.6 2285.39
     128 2286.68   140.7 2286.24   152.9 2286.36   165.1  2285.5   173.3 2285.44
   181.4 2285.65   185.5 2286.37   189.6 2288.62   193.6 2291.69   197.7 2295.17
   205.8 2302.66   209.9    2306   216.3 2311.72   234.3 2326.52   254.1 2340.72
#Mann= 4, -1 ,  0
       0     0.1       0   96.18   0.045       0  115.76     0.1       0
  205.87    0.06       0
Bank Sta=96.18,115.76
XS Rating Curve= 0 ,0
Exp/Cntr=0.3,0.1