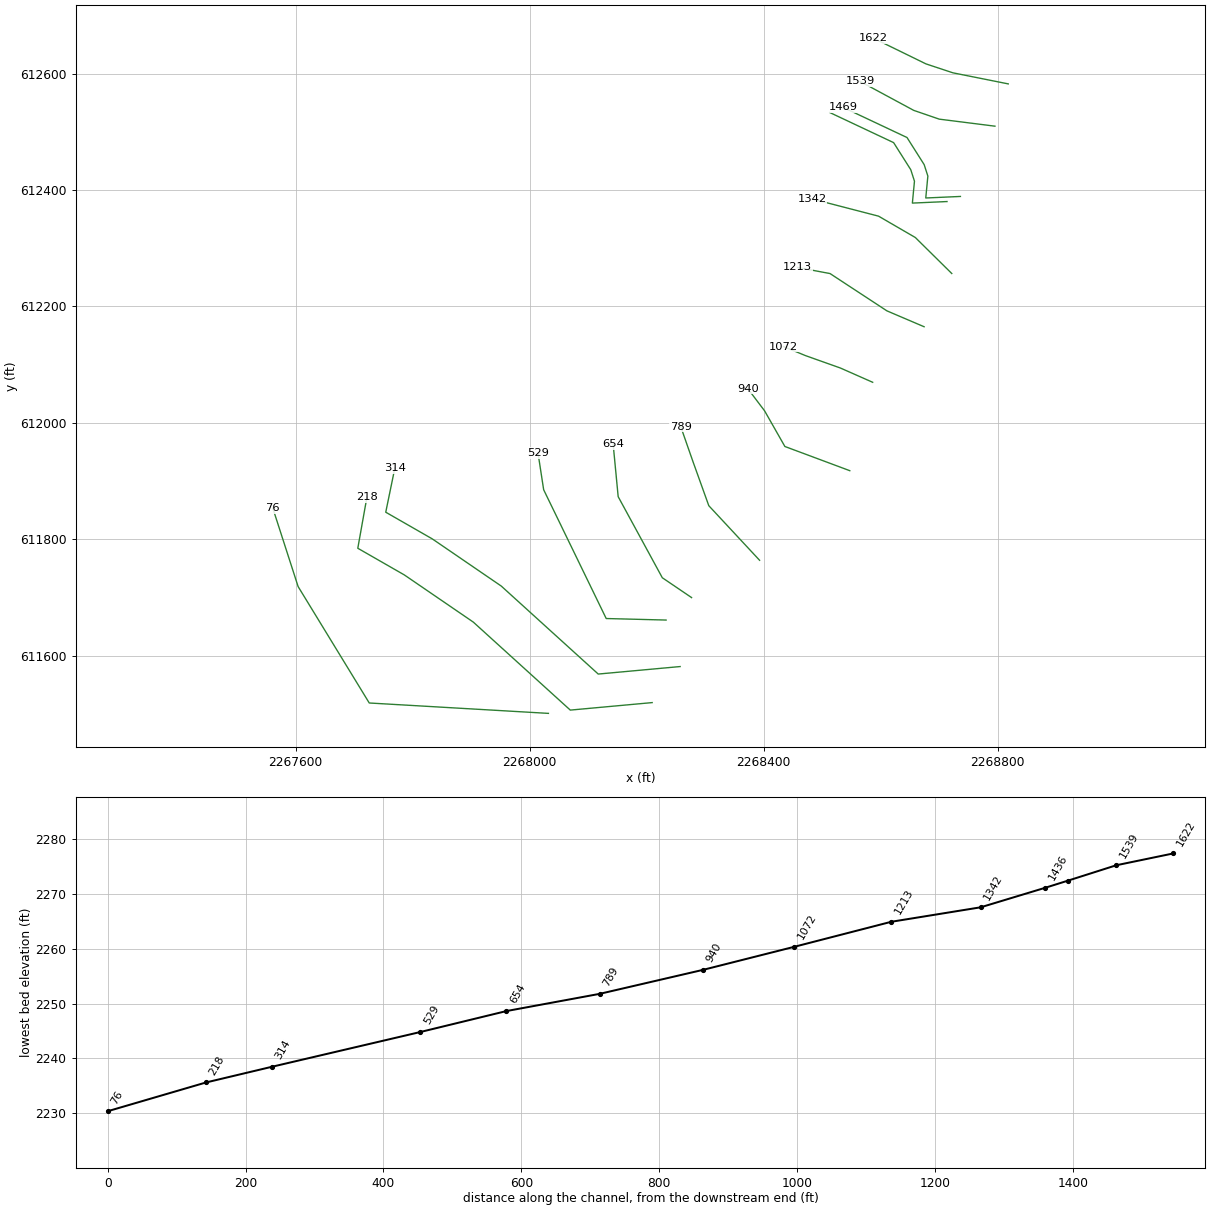
HEC-RAS study LAURELRN5.prj: LAURELRN5

--- LAURELRN5.g01 (geometry) --- (continued)

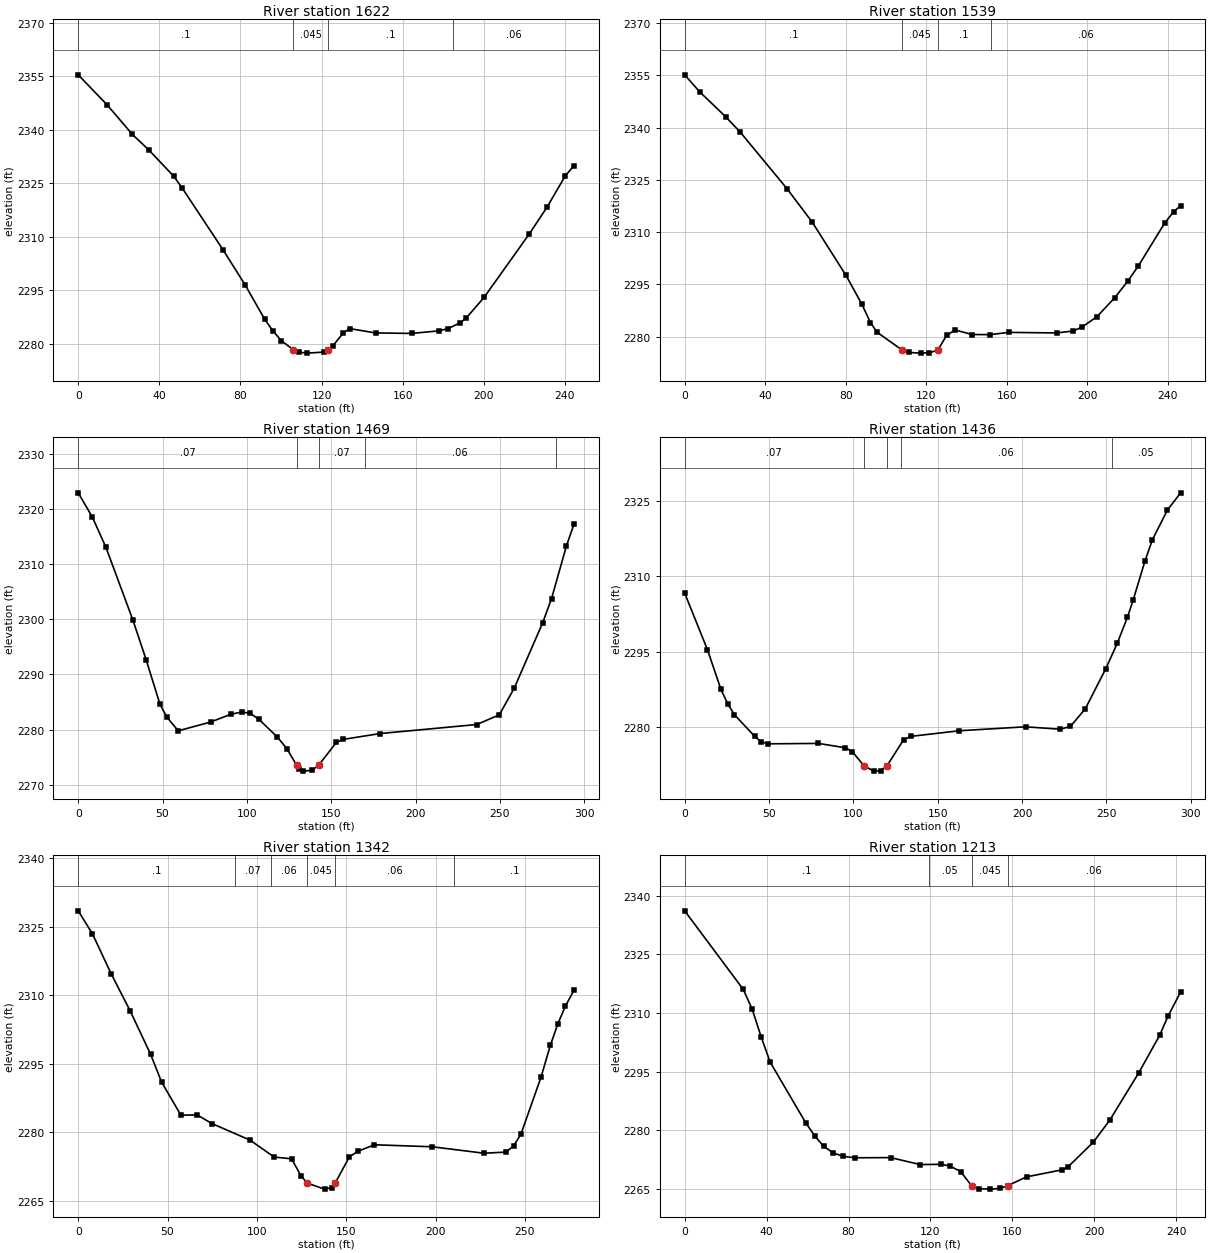
Type RM Length L Ch R = 1 ,1622    ,82.8,82.8,82.6
XS GIS Cut Line= 4
2268818.32805594612582.3453914962268723.67658432612601.381441653
2268677.67279644612616.7160376132268588.30911654612660.604708808
#Sta/Elev= 30
       0 2355.38    14.4 2346.88    26.7  2338.7    34.8 2334.35    47.1 2326.99
    51.2 2323.75    71.6 2306.23    82.4 2296.48      92 2286.89      96  2283.7
   100.2 2280.91  106.012278.443   108.7 2277.72   112.9 2277.45   121.3 2277.75
  123.252278.445   125.5 2279.41   130.8 2283.15     134 2284.31   146.7  2283.1
   164.5 2282.97   177.9 2283.69   182.4 2284.31   188.3 2285.93   191.3 2287.23
   200.2 2293.08   222.5 2310.84   231.4 2318.49   240.3 2327.17   244.6 2329.98
#Mann= 4, -1 ,  0
       0     0.1       0  106.01   0.045       0  123.25     0.1       0
  185.04    0.06       0
Bank Sta=106.01,123.25
XS Rating Curve= 0 ,0
Exp/Cntr(USF)=0,0
Exp/Cntr=0.3,0.1

Type RM Length L Ch R = 1 ,1539    ,75.1,69.9,67.5
XS GIS Cut Line= 4
2268795.60666457612509.7200443022268700.34827197612521.811461347
2268656.86070915 612536.816392872268565.11646542612586.543314893
#Sta/Elev= 30
       0 2355.19     7.5 2350.28    20.5 2343.08    27.7 2338.67    50.8 2322.53
    63.4 2312.87    80.1 2297.66    88.1 2289.26    92.3 2284.04    95.6 2281.28
   108.12276.145   111.4 2275.48   117.4 2275.29   121.6 2275.41  125.772276.144
   130.1 2280.36   134.3 2281.95   142.8 2280.63   151.9  2280.6     161 2281.25
   184.8 2281.08     193 2281.64   197.4 2282.78   204.8 2285.73   213.6 2291.15
   220.2 2295.99   225.4 2300.33   238.4 2312.56   242.9 2315.87   246.4 2317.62
#Mann= 4, -1 ,  0
       0     0.1       0   108.1   0.045       0  125.77     0.1       0
  152.03    0.06       0
Bank Sta=108.1,125.77
XS Rating Curve= 0 ,0
Exp/Cntr(USF)=0,0
Exp/Cntr=0.3,0.1

Type RM Length L Ch R = 1 ,1469    ,32.9,33.4,30.7
XS GIS Cut Line= 6
2268736.54135859612389.0145134042268677.31809143612386.370617549
2268680.90390776612423.983671975 2268674.5810718612443.710920161
2268645.24311296612490.2469928062268536.03622238612541.977257326
#Sta/Elev= 30
       0 2322.88     8.4 2318.47    16.4 2313.04    32.4 2299.86    40.4 2292.54
    48.4 2284.66    52.4 2282.32    59.3 2279.79    78.5 2281.38    90.5 2282.79
    97.3  2283.2     102 2282.93     107 2281.91   118.1 2278.64   123.8 2276.52
  129.452273.554   131.1  2272.8   133.5 2272.49   138.5 2272.64  142.542273.552
     153 2277.68   156.9 2278.23   179.1  2279.3   236.3 2280.93   249.6 2282.68
   258.4 2287.46   275.3 2299.32   280.6 2303.73   289.4 2313.25     294 2317.29
#Mann= 5, -1 ,  0
       0    0.07       0  129.45   0.045       0  142.54    0.07       0
  169.79    0.06       0  283.14    0.05       0
Bank Sta=129.45,142.54
XS Rating Curve= 0 ,0
Exp/Cntr(USF)=0,0
Exp/Cntr=0.3,0.1

Type RM Length L Ch R = 1 ,1436    ,90.3,93.5,98.3
XS GIS Cut Line= 6
2268713.64726581612380.2584227152268654.42399865612377.614526859
2268658.00981498612415.2275812852268651.68697902612434.954829471
2268622.34902018612481.490902117 2268513.1421296612533.221166636
#Sta/Elev= 30
       0 2306.63    13.5 2295.36    21.5 2287.45    25.5 2284.59    29.5  2282.4
    41.5 2278.11    45.5 2276.98    49.5 2276.61    79.3 2276.69    95.3 2275.82
    99.4 2275.05  106.272272.246     112 2271.17   116.3 2271.26  119.992272.243
   129.8 2277.44     134 2278.09   162.7 2279.21   202.1    2280   222.6 2279.52
   228.7 2280.08   237.5 2283.59   249.6 2291.55   256.5 2296.68   262.5 2301.85
   265.9 2305.29   272.9 2313.06   277.3 2317.29   286.2 2323.19     294 2326.61
#Mann= 5, -1 ,  0
       0    0.07       0  106.27   0.045       0  119.99    0.07       0
  128.05    0.06       0  253.14    0.05       0
Bank Sta=106.27,119.99
XS Rating Curve= 0 ,0
Exp/Cntr(USF)=0,0
Exp/Cntr=0.3,0.1

Type RM Length L Ch R = 1 ,1342    ,129.9,129.5,129.1
XS GIS Cut Line= 4
  2268721.758372612256.6624532712268659.41530774612318.529616282
2268596.59634222612355.1740128352268483.33184378612384.679890579
#Sta/Elev= 30
       0 2328.46     7.9 2323.48    18.5 2314.65    29.1 2306.57    40.5 2297.11
    46.7 2290.99    57.5 2283.76    66.5 2283.85      75 2281.92    96.2 2278.32
   109.7 2274.62   119.4 2274.24   124.8 2270.45  128.312268.906   137.9 2267.61
   141.9 2267.93  143.782268.903   151.8 2274.66   156.6  2275.9   165.8 2277.31
   198.2 2276.87   227.1 2275.46   239.5 2275.71   243.7 2277.06   247.8 2279.62
     259 2292.02   264.3 2299.08   268.5 2303.77   272.6 2307.55   277.6 2311.18
#Mann= 6, -1 ,  0
       0     0.1       0   87.83    0.07       0  107.83    0.06       0
  128.31   0.045       0  143.78    0.06       0  210.56     0.1       0
Bank Sta=128.31,143.78
XS Rating Curve= 0 ,0
Exp/Cntr(USF)=0,0
Exp/Cntr=0.3,0.1

Type RM Length L Ch R = 1 ,1213    ,139.7,141.1,143.2
XS GIS Cut Line= 4
2268674.49480897612165.2212181762268610.90436352 612192.49902314
2268513.68067959612256.5651136642268458.19143481612267.062095524
#Sta/Elev= 30
       0  2336.1    28.6 2316.02      33 2310.89    37.3 2303.94    41.7 2297.45
    59.1 2281.92    63.5 2278.57    67.8 2275.92    72.5 2274.23    77.4 2273.34
    83.2 2272.98   100.5 2273.03     115 2271.25   125.2 2271.31   129.4  2270.9
   134.7 2269.47  140.03 2265.86   143.8 2265.08   149.1 2264.97   153.9 2265.14
   157.7 2265.86   166.9 2268.11   184.3 2269.91   187.2 2270.69   199.4 2276.93
   207.5 2282.58   221.7 2294.73   231.9 2304.31     236 2309.25   242.1 2315.35
#Mann= 4, -1 ,  0
       0     0.1       0  119.19    0.05       0  140.03   0.045       0
   157.7    0.06       0
Bank Sta=140.03,157.7
XS Rating Curve= 0 ,0
Exp/Cntr=0.3,0.1

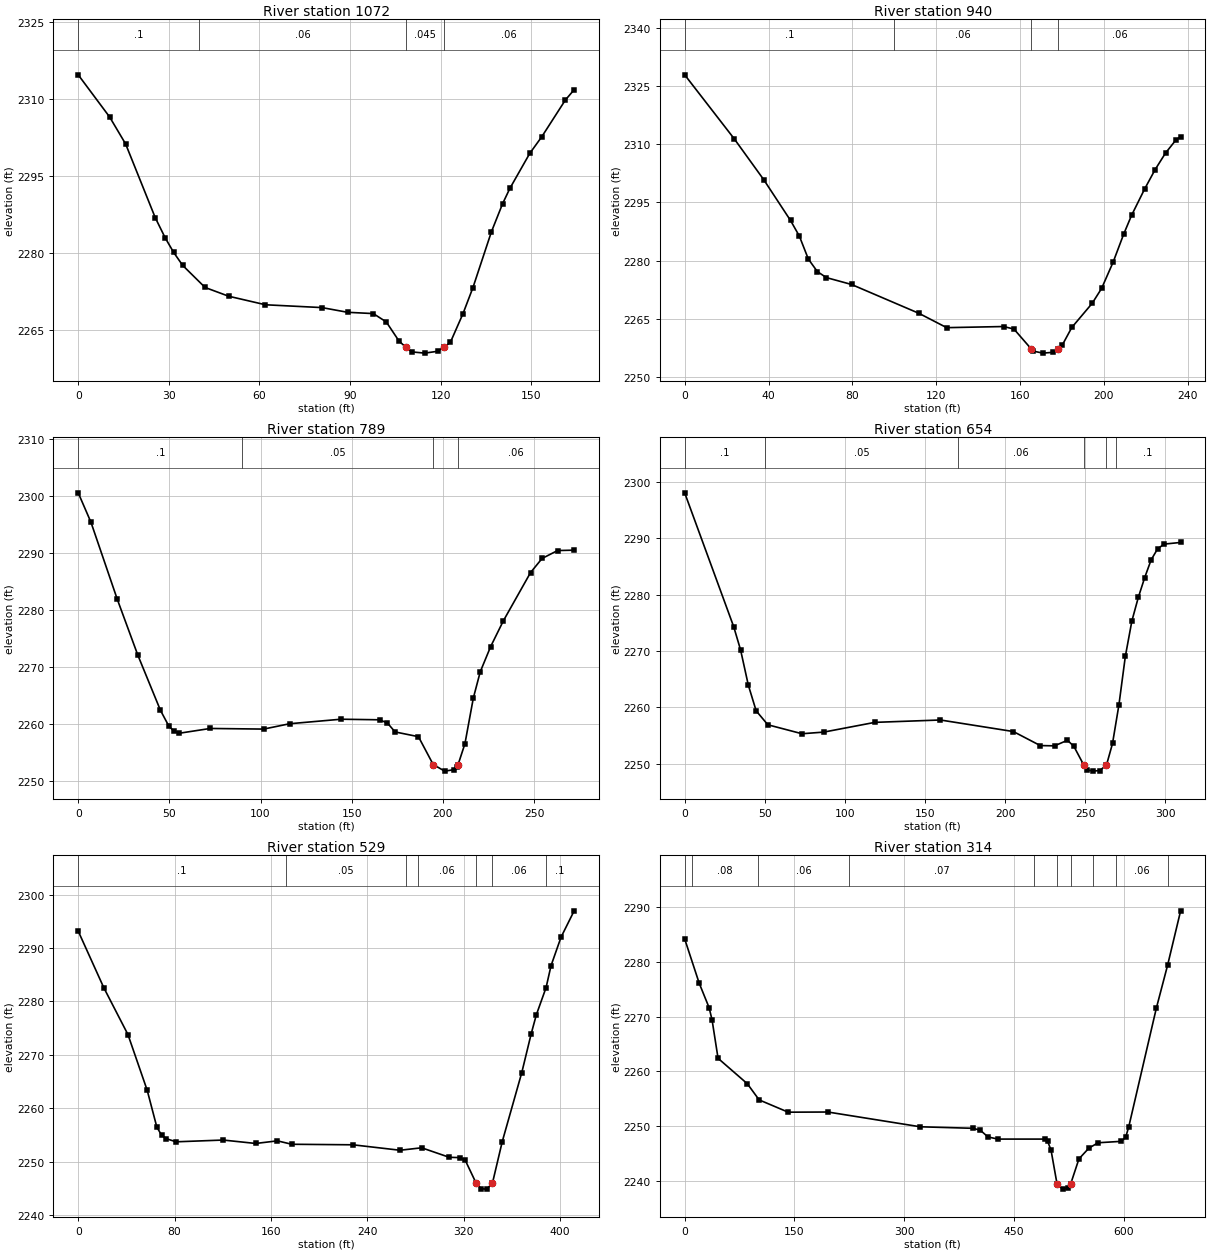
Type RM Length L Ch R = 1 ,1072    ,136.4,131.7,127.3
XS GIS Cut Line= 4
2268586.53194527612069.8160929462268531.40798618612094.302457485
2268471.62716331612115.6507558722268434.27052404612131.138854944
#Sta/Elev= 30
       0 2314.72    10.4 2306.49    15.7 2301.22    25.5 2286.84    28.8 2282.89
    31.6 2280.05    34.6 2277.51      42 2273.21    49.8  2271.5      62 2269.83
    80.7 2269.28    89.2 2268.36    97.7 2268.11     102 2266.48   106.2 2262.76
  108.522261.514   110.5 2260.63   114.7 2260.39     119 2260.75  121.042261.514
   123.2 2262.47   127.4  2268.1   130.7  2273.2   136.8 2284.07   140.5 2289.55
   142.9 2292.53   149.5 2299.38   153.5 2302.65   161.3 2309.81   164.2 2311.81
#Mann= 4, -1 ,  0
       0     0.1       0      40    0.06       0  108.52   0.045       0
  121.04    0.06       0
Bank Sta=108.52,121.04
XS Rating Curve= 0 ,0
Exp/Cntr=0.3,0.1

Type RM Length L Ch R = 1 ,940     ,152.1,150.6,149.7
XS GIS Cut Line= 4
2268547.43793798611917.9706289862268436.50535569611959.516808454
2268401.81215427612020.7652998352268373.11530866612058.884990275
#Sta/Elev= 30
       0 2327.87    23.7 2311.35    37.7 2300.88    50.5 2290.36    54.7 2286.35
      59 2280.42    63.3  2277.2    67.6 2275.65    79.6 2273.88   111.8 2266.44
     125 2262.76   152.2 2263.05   157.1 2262.39  165.35 2257.27   166.3 2256.72
   170.9  2256.2   175.5  2256.4  178.142257.271   180.1 2258.23   184.7 2262.82
   194.4 2269.02   198.9 2272.86   204.4 2279.63   209.4 2286.79   213.2 2291.69
   219.4 2298.44   224.4 2303.43   229.4 2307.73   234.4 2311.12   236.6 2311.94
#Mann= 4, -1 ,  0
       0     0.1       0     100    0.06       0  165.35   0.045       0
  178.14    0.06       0
Bank Sta=165.35,178.14
XS Rating Curve= 0 ,0
Exp/Cntr(USF)=0,0
Exp/Cntr=0.3,0.1

Type RM Length L Ch R = 1 ,789     ,137.2,135.1,133.8
XS GIS Cut Line= 4
2268393.26882158611764.050674979 2268306.4579104611857.801049979
2268279.07014681  611934.44489512268258.43981299611993.755431676
#Sta/Elev= 30
       0 2300.59       7 2295.42    21.4 2281.95    32.7 2272.13    45.1 2262.46
    49.7  2259.7    52.5  2258.8    55.4 2258.44    72.4 2259.28   101.7 2259.17
     116 2260.11   144.1  2260.9   165.3  2260.8   169.6 2260.23   173.8 2258.67
   186.6 2257.84   194.72252.951     201  2251.8   205.9 2252.04   207.8 2252.45
  208.352252.949   212.1 2256.61   216.7 2264.61   220.5 2269.22   226.2 2273.63
   233.2 2278.17   248.1 2286.62   254.4 2289.08   262.9 2290.47     272 2290.54
#Mann= 4, -1 ,  0
       0     0.1       0      90    0.05       0   194.7   0.045       0
  208.35    0.06       0
Bank Sta=194.7,208.35
XS Rating Curve= 0 ,0
Exp/Cntr=0.3,0.1

Type RM Length L Ch R = 1 ,654     ,122.2,124.7,127.1
XS GIS Cut Line= 4
2268277.02684925 611699.979492192268226.97779191611734.070879074
2268151.54153157611873.3378212412268142.95359278611963.522411587
#Sta/Elev= 30
       0 2298.08    30.6  2274.3    34.9 2270.17    39.7 2263.95    44.6 2259.37
    51.9 2256.89    73.2  2255.3    86.8 2255.59   118.7 2257.32   159.6 2257.74
   205.1 2255.69   221.9  2253.2   230.8 2253.15   238.9 2254.14   242.9 2253.05
  249.092249.724   250.9 2248.89   254.9 2248.66     259 2248.77  263.222249.722
     267 2253.57     271 2260.43     275 2269.04   279.1 2275.35   283.1 2279.51
   287.1 2283.04   291.1 2286.18   295.1 2288.11   299.1 2288.97   309.5 2289.27
#Mann= 6, -1 ,  0
       0     0.1       0      50    0.05       0  170.56    0.06       0
  249.09   0.045       0  263.22    0.06       0  268.94     0.1       0
Bank Sta=249.09,263.22
XS Rating Curve= 0 ,0
Exp/Cntr(USF)=0,0
Exp/Cntr=0.3,0.1

Type RM Length L Ch R = 1 ,529     ,210.5,215.7,220.7
XS GIS Cut Line= 4
 2268233.4596803611661.3928444822268131.07921789611664.015503667
2268024.17090341611885.240089718 2268014.5244598611948.233272567
#Sta/Elev= 30
       0 2293.15    21.3 2282.53    41.3 2273.78    57.3 2263.33    65.3 2256.44
    69.3 2254.92    73.3 2254.27    81.3  2253.7   120.4 2254.03   147.4 2253.39
   165.4 2253.88   177.3 2253.24   228.1 2253.14   267.2 2252.12   285.2 2252.58
   308.1  2250.8     317 2250.74   321.4 2250.23  330.512245.906   334.7 2244.91
   339.1 2244.84   343.9 2245.91   352.1 2253.74   368.3 2266.65   376.1 2273.91
   380.4 2277.48   388.5 2282.59   392.6 2286.68   400.9 2292.01   411.8 2296.95
#Mann= 7, -1 ,  0
       0     0.1       0  172.41    0.05       0  272.41    0.07       0
  282.41    0.06       0  330.51   0.045       0   343.9    0.06       0
  388.12     0.1       0
Bank Sta=330.51,343.9
XS Rating Curve= 0 ,0
Exp/Cntr=0.3,0.1

Type RM Length L Ch R = 1 ,314     ,95.2,95.4,95.3
XS GIS Cut Line= 6
  2268257.427797611581.5117618532268117.45993874611568.625408428
2267951.65003027611719.8037578622267833.86446992611800.754561157
2267754.24326618611846.6341983612267769.81567774611922.602078254
#Sta/Elev= 30
       0 2284.23    19.8 2276.15    33.4 2271.65    37.4 2269.43    45.6  2262.4
    85.6 2257.75   101.7  2254.8   141.4 2252.55   195.6 2252.58   321.8 2249.88
   394.2  2249.6   404.1 2249.23   414.2 2248.03   427.8 2247.63   492.2 2247.63
   495.7 2247.27   500.5  2245.6  508.722239.391   516.4 2238.48   524.1 2238.72
   527.22239.388   538.6 2244.01   552.2 2245.98   564.8 2246.96   596.7 2247.22
   602.5 2248.01   606.6 2249.85   644.4 2271.61   659.7 2279.42   677.5 2289.37
#Mann= 10, -1 ,  0
       0     0.1       0      10    0.08       0     100    0.06       0
   225.1    0.07       0  477.79    0.06       0  508.72   0.045       0
   527.2    0.06       0  557.98     0.1       0  588.72    0.06       0
  659.94     0.1       0
Bank Sta=508.72,527.2
XS Rating Curve= 0 ,0
Exp/Cntr(USF)=0,0
Exp/Cntr=0.3,0.1

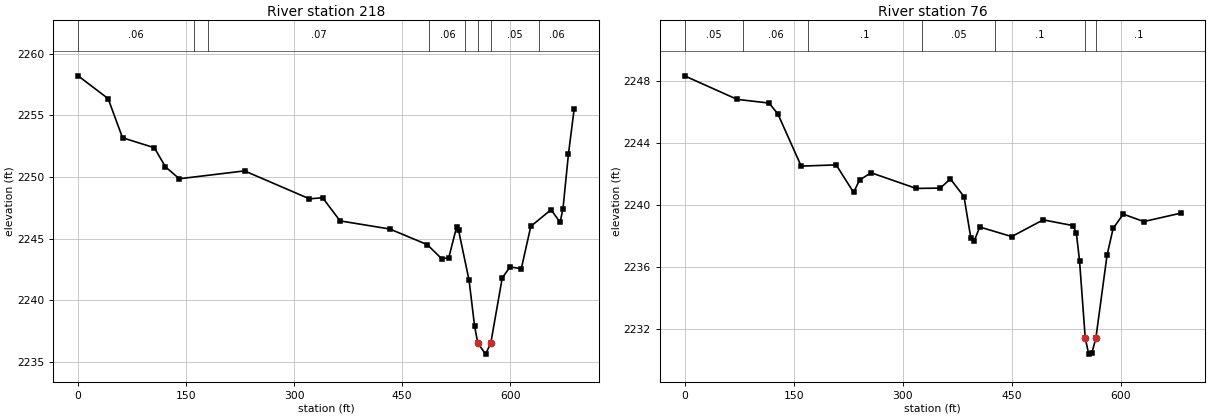
Type RM Length L Ch R = 1 ,218     ,149,142.6,137.1
XS GIS Cut Line= 6
2268209.65981939  611519.60156072268069.69196113611506.715207275
2267903.88205267 611657.893556712267786.09649232611738.844360004
2267706.47528858611784.7239972092267722.04770014611872.442525347
#Sta/Elev= 30
       0 2258.22    41.7 2256.37    61.7 2253.19   105.9 2252.38   121.3 2250.83
   140.6 2249.86   231.2  2250.5   321.4 2248.23   339.6 2248.32   363.9 2246.44
     433 2245.78     485 2244.51   505.3 2243.35   514.9 2243.46   525.6 2245.91
   528.5 2245.67   543.1  2241.6   550.7  2237.9  555.162236.518     566 2235.62
  573.222236.518   589.1  2241.8   599.9  2242.7   615.6 2242.56   628.8    2246
     657 2247.35   669.5 2246.32   673.5 2247.44   681.1 2251.87     689 2255.52
#Mann= 8, -1 ,  0
       0    0.06       0  160.56    0.05       0  180.56    0.07       0
  487.79    0.06       0  537.98    0.05       0  555.16   0.045       0
  573.22    0.05       0  639.94    0.06       0
Bank Sta=555.16,573.22
XS Rating Curve= 0 ,0
Exp/Cntr(USF)=0,0
Exp/Cntr=0.3,0.1

Type RM Length L Ch R = 1 ,76      ,,,
XS GIS Cut Line= 4
2268032.32584136611501.0890947252267726.04097696611518.937185525
2267604.46094165611718.8780955082267561.22002494611853.516811592
#Sta/Elev= 30
       0 2248.34    72.3 2246.82   116.3 2246.58   128.4 2245.87   160.4 2242.51
   208.5 2242.59   232.5 2240.81   240.6 2241.61   256.6 2242.08   318.5 2241.07
   351.6 2241.09   365.6 2241.68   384.3 2240.54   393.7 2237.87   398.4 2237.68
   405.9 2238.58   449.9 2237.96   493.2 2239.04   534.1 2238.67   538.8 2238.19
   543.2  2236.4  551.032231.404   555.8 2230.37     560 2230.42  565.682231.407
     581 2236.75   589.4 2238.49   603.3 2239.41   631.5 2238.93   682.2 2239.47
#Mann= 7, -1 ,  0
       0    0.05       0      80    0.06       0     170     0.1       0
   326.8    0.05       0   426.8     0.1       0  551.03   0.045       0
  565.68     0.1       0
Bank Sta=551.03,565.68
XS Rating Curve= 0 ,0
Exp/Cntr(USF)=0,0
Exp/Cntr=0.3,0.1
LCMann Table=0

Chan Stop Cuts=-1
Use User Specified Reach Order=0
Composite Channel Slope=5